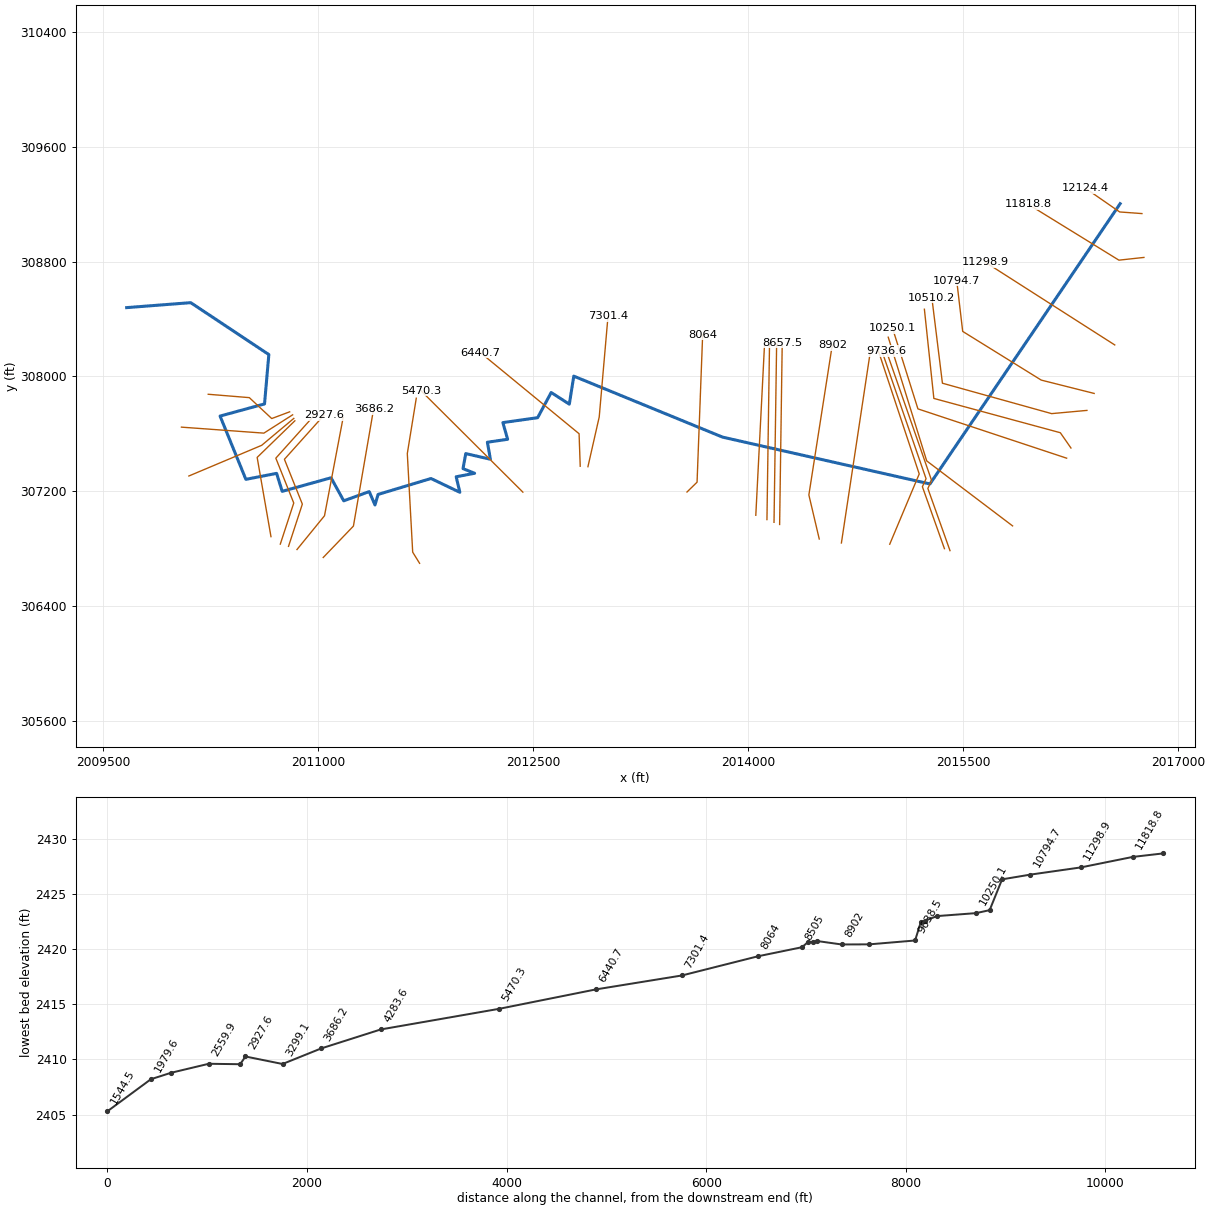
--- COONCK.prj (project) ---

Proj Title=COONCK
Current Plan=p01
Default Exp/Contr=0,0
English Units
Geom File=g01
Flow File=f01
Plan File=p01
BEGIN DESCRIPTION:
END DESCRIPTION:
DSS Export Rating Curves= 0
DSS Export Rating Curve Sorted= 0
DSS Export Volume Flow Curves= 0
DXF OffsetX= 0
DXF OffsetY= 0
DXF ScaleX= 0
DXF ScaleY= 0

--- COONCK.p01 (plan) ---

Plan Title=Floodplain
Program Version=4.00
Geom File=g01
Flow File=f01
K Sum by GR=0
Std Step Tol=0.01
Critical Tol=0.01
Num of Std Step Trials=20
Max Error Tol=0.3
Flow Tol Ratio=0.001
Split Flow NTrial=30
Split Flow Tol=0.02
Split Flow Ratio=0.02
Log Output Level=0
Friction Slope Method=1
Unsteady Friction Slope Method=2
Unsteady Bridges Friction Slope Method=1
Global Log Level=0
CheckData=False
Run HTab=0
Run UNet=0
Run PostProcess=0
UNET Theta=0
UNET Theta Warmup=0
UNET ZTol=0
UNET ZSATol=0
UNET MxIter=0
UNET MaxInSteps=0
UNET DtIC=0
UNET DtMin=0
UNET MaxCRTS=0
UNET WFStab=0
UNET SFStab=0
UNET WFX=0
UNET SFX=0
UNET DSS MLevel=0
UNET DZMax Abort=0
UNET Convert EG Bridges=0
UNET Use Existing IB Tables=0
UNET Froude Limit=0
UNET Froude Power=0
Write IC File=0
Echo Input=False
Echo Output=False
Write Detailed=0

--- COONCK.f01 (steady flow) ---

Flow Title=2010 USGS WV Regression Equation
Program Version=4.00
Number of Profiles=1
Profile Names=P100yr
River Rch & RM=COONCK,Main      ,12124.4
518.7624
River Rch & RM=COONCK,Main      ,10794.7
596.1033
River Rch & RM=COONCK,Main      ,10794.7
527.4183
River Rch & RM=COONCK,Main      ,9856.7
602.3248
River Rch & RM=COONCK,Main      ,8064
668.3625
River Rch & RM=COONCK,Main      ,7301.4
721.6994
River Rch & RM=COONCK,Main      ,3299.1
775.8110
River Rch & RM=COONCK,Main      ,249.1
853.1061
Boundary for River Rch & Prof#=COONCK,Main      ,1
Up Type=0
Dn Type=3
Dn Slope=0.155295

--- COONCK.g01 (geometry) ---

Geom Title=LiDAR
Program Version=4.10

River Reach=COONCK          ,Main
Reach XY= 30
     2016594.661      309203.786     2015268.289      307250.581
     2013821.981       307576.91      2012784.22      308001.824
     2012752.967      307806.576     2012626.578      307887.826
     2012532.133      307712.479     2012289.425      307678.104
     2012322.758      307561.785     2012181.583      307541.424
     2012202.575       307422.79     2012030.846      307462.187
     2012011.531      307357.369     2012092.666      307325.034
      2011964.02      307300.555     2011989.541      307192.395
     2011788.325      307288.576     2011419.402      307177.638
     2011397.527      307104.374     2011357.509      307197.256
     2011179.645      307132.933     2011091.364      307293.611
     2010750.478      307199.079     2010711.416       307324.34
     2010497.093      307282.673     2010317.363      307723.588
     2010627.313      307808.316     2010657.371      308152.395
      2010112.68       308513.99     2009665.733      308479.493

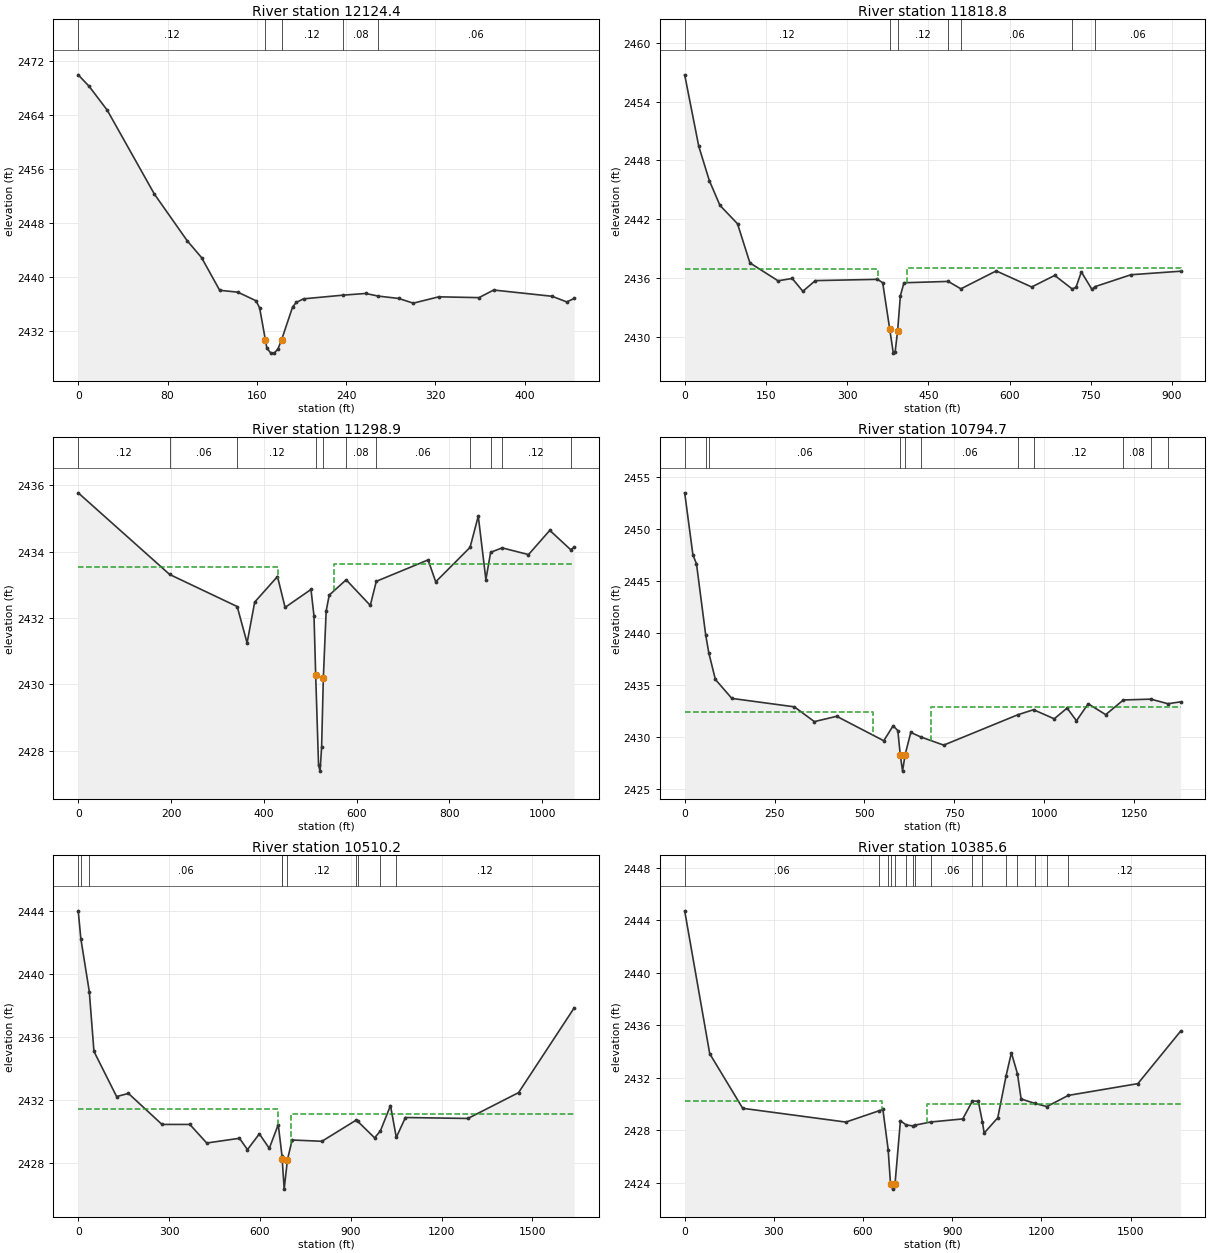
Type RM Length L Ch R = 1 ,12124.4 ,305.2,305.6,302.9
XS GIS Cut Line= 3
      2016746.85      309134.848     2016591.321      309146.219
     2016354.341      309310.282
#Sta/Elev= 30
       0 2469.98     9.8 2468.27      26 2464.73    68.2 2452.28    97.5 2445.37
   110.5 2442.84   126.7 2437.99     143 2437.71   159.2 2436.44   162.5 2435.37
  167.672430.607     169 2429.39   172.3 2428.71   175.6 2428.66   178.9 2429.28
   182.2 2430.66     192  2435.5   195.2 2436.18   201.8 2436.72  236.952437.264
   257.5 2437.52  268.752437.127     287 2436.78   300.1 2436.08     323 2437.02
     359  2436.9   372.1 2438.03   424.5  2437.1   437.6 2436.26   444.2 2436.78
#Mann= 5 ,-1 , 0
       0     .12       0  167.67    .045       0   182.2     .12       0
  236.95     .08       0  268.75     .06       0
Bank Sta=167.67,182.2
XS Rating Curve= 0 ,0
Exp/Cntr=0.3,0.1

Type RM Length L Ch R = 1 ,11818.8 ,517.2,519.9,518.5
XS GIS Cut Line= 3
     2016760.739      308829.292     2016586.112      308810.282
     2015955.904      309198.303
#Sta/Elev= 30
       0 2456.74      26 2449.45    45.5 2445.95    65.1 2443.42    97.6 2441.54
   120.4 2437.55   172.4 2435.72   198.6 2435.96   218.2 2434.65   241.2 2435.74
   355.8 2435.87   365.6 2435.53   378.7 2430.76   385.2 2428.34   388.5 2428.43
   393.12430.578   398.3 2434.21   404.9 2435.52  486.582435.659  509.982434.903
   575.2 2436.73   640.7 2435.09   683.2 2436.27  715.352434.896   722.5 2435.05
   732.4 2436.63     752 2434.84  757.31 2435.12     824 2436.34   915.7  2436.7
#Mann= 7 ,-1 , 0
       0     .12       0   378.7    .045       0   393.1     .12       0
  486.58     .08       0  509.98     .06       0  715.35    .016       0
  757.31     .06       0
#XS Ineff= 2 , 0
          356.04 2436.88  410.73            2437
Permanent Ineff=
       F       F
Bank Sta=378.7,393.1
XS Rating Curve= 0 ,0
Exp/Cntr=0.3,0.1

Type RM Length L Ch R = 1 ,11298.9 ,500.4,504.2,500.7
XS GIS Cut Line= 2
     2016557.186      308219.315     2015656.572       308794.57
#Sta/Elev= 30
       0 2435.77  197.142433.311  342.612432.346   363.9 2431.25   380.3 2432.48
   429.4 2433.25   445.8 2432.32   501.6 2432.86   508.1 2432.06  511.732430.277
   517.9 2427.57   521.2 2427.39   524.5 2428.11   528.2 2430.19   534.3 2432.21
   540.9 2432.69  577.422433.151   629.4 2432.38   642.32433.105     754 2433.75
   770.4 2433.09   844.42434.128   862.1 2435.07   878.5 2433.16  888.752433.979
  913.532434.113   970.3 2433.91  1016.2 2434.64 1061.01 2434.06  1068.7 2434.13
#Mann= 11 ,-1 , 0
       0     .12       0  197.14     .06       0  342.61     .12       0
  511.73    .045       0   528.2     .12       0  577.42     .08       0
   642.3     .06       0   844.4    .016       0  888.75     .06       0
  913.53     .12       0 1061.01     .06       0
#XS Ineff= 2 , 0
          430.96 2433.53  551.08         2433.64
Permanent Ineff=
       F       F
Bank Sta=511.73,528.2
XS Rating Curve= 0 ,0
Exp/Cntr=0.3,0.1

Type RM Length L Ch R = 1 ,10794.7 ,276.8,284.4,290.5
XS GIS Cut Line= 4
     2016413.425      307881.424     2016044.446      307974.344
     2015496.614      308313.684     2015455.183      308666.098
#Sta/Elev= 30
       0 2453.49      23 2447.51    32.8 2446.68   58.362439.854   67.11 2438.11
    85.3 2435.56   131.2 2433.73   305.1 2432.92   360.8  2431.5     423 2432.01
   553.9 2429.66     580  2431.1   593.1 2430.63   599.7 2428.32   606.2 2426.74
  613.182428.305   629.1 2430.46  657.17 2430.02   720.7 2429.24  927.132432.161
  970.562432.643  1028.2 2431.77    1064  2432.8    1090 2431.58  1122.6 2433.21
  1171.4 2432.17 1220.51 2433.58 1296.68 2433.66 1344.52 2433.22  1379.8  2433.4
#Mann= 11 ,-1 , 0
       0    .016       0   58.36     .08       0   67.11     .06       0
   599.7    .045       0  613.18     .12       0  657.17     .06       0
  927.13    .016       0  970.56     .12       0 1220.51     .08       0
 1296.68     .12       0 1344.52     .06       0
#XS Ineff= 2 , 0
          524.46  2432.4  686.27         2432.91
Permanent Ineff=
       F       F
Bank Sta=599.7,613.18
XS Rating Curve= 0 ,0
Exp/Cntr=0.3,0.1

Type RM Length L Ch R = 1 ,10510.2 ,123.9,124.6,124
XS GIS Cut Line= 4
     2016363.099       307763.14     2016116.918      307740.711
     2015355.209      307952.643     2015281.572      308548.042
#Sta/Elev= 30
       0 2443.99    8.722442.216   36.572438.863      52 2435.06   126.8 2432.19
   165.9 2432.39   276.7 2430.42   368.6 2430.42   424.4 2429.24   532.6 2429.54
   558.9 2428.82   598.2 2429.82     631  2428.9   660.6 2430.41  673.172428.396
   673.7 2428.21   680.2 2426.31  690.982428.183   706.5 2429.43   804.9 2429.35
  918.682430.703   923.12430.617   978.8 2429.57  997.742430.001  1031.3 2431.62
 1050.452429.594  1080.5 2430.86    1287  2430.8  1454.2 2432.44  1637.8 2437.82
#Mann= 10 ,-1 , 0
       0     .06       0    8.72    .016       0   36.57     .06       0
  673.17     .12       0   673.7    .045       0  690.98     .12       0
  918.68     .06       0   923.1     .12       0  997.74    .016       0
 1050.45     .12       0
#XS Ineff= 2 , 0
           661.3 2431.42  702.17         2431.11
Permanent Ineff=
       F       F
Bank Sta=673.7,690.98
XS Rating Curve= 0 ,0
Exp/Cntr=0.3,0.1

Type RM Length L Ch R = 1 ,10385.6 ,136.1,135.5,133.4
XS GIS Cut Line= 4
     2016251.605      307501.087     2016177.545      307607.584
     2015295.461      307846.654     2015229.489      308468.181
#Sta/Elev= 30
       0 2444.73    84.3 2433.84   195.2 2429.68   542.4 2428.63  654.942429.498
   666.9 2429.59  684.58 2426.54  692.522423.929   699.7 2423.52  707.742423.932
   725.9 2428.73  745.792428.406  767.852428.343  776.392428.402  827.792428.637
   935.5 2428.87  968.172430.236   987.9 2430.22    10022428.619  1007.6 2427.79
  1053.4 2428.96 1081.632432.178  1099.2 2433.91 1119.592432.321    1132 2430.39
    11792430.049 1218.562429.813 1290.742430.663  1524.7 2431.56  1668.6 2435.56
#Mann= 16 ,-1 , 0
       0     .06       0  654.94     .12       0  684.58    .016       0
  692.52    .045       0  707.74    .016       0  745.79     .12       0
  767.85     .06       0  776.39     .12       0  827.79     .06       0
  968.17    .016       0    1002     .06       0 1081.63    .016       0
 1119.59     .06       0    1179     .12       0 1218.56     .08       0
 1290.74     .12       0
#XS Ineff= 2 , 0
          665.54 2430.21  816.27         2429.97
Permanent Ineff=
       F       F
Bank Sta=692.52,707.74
XS Rating Curve= 0 ,0
Exp/Cntr=0.3,0.1

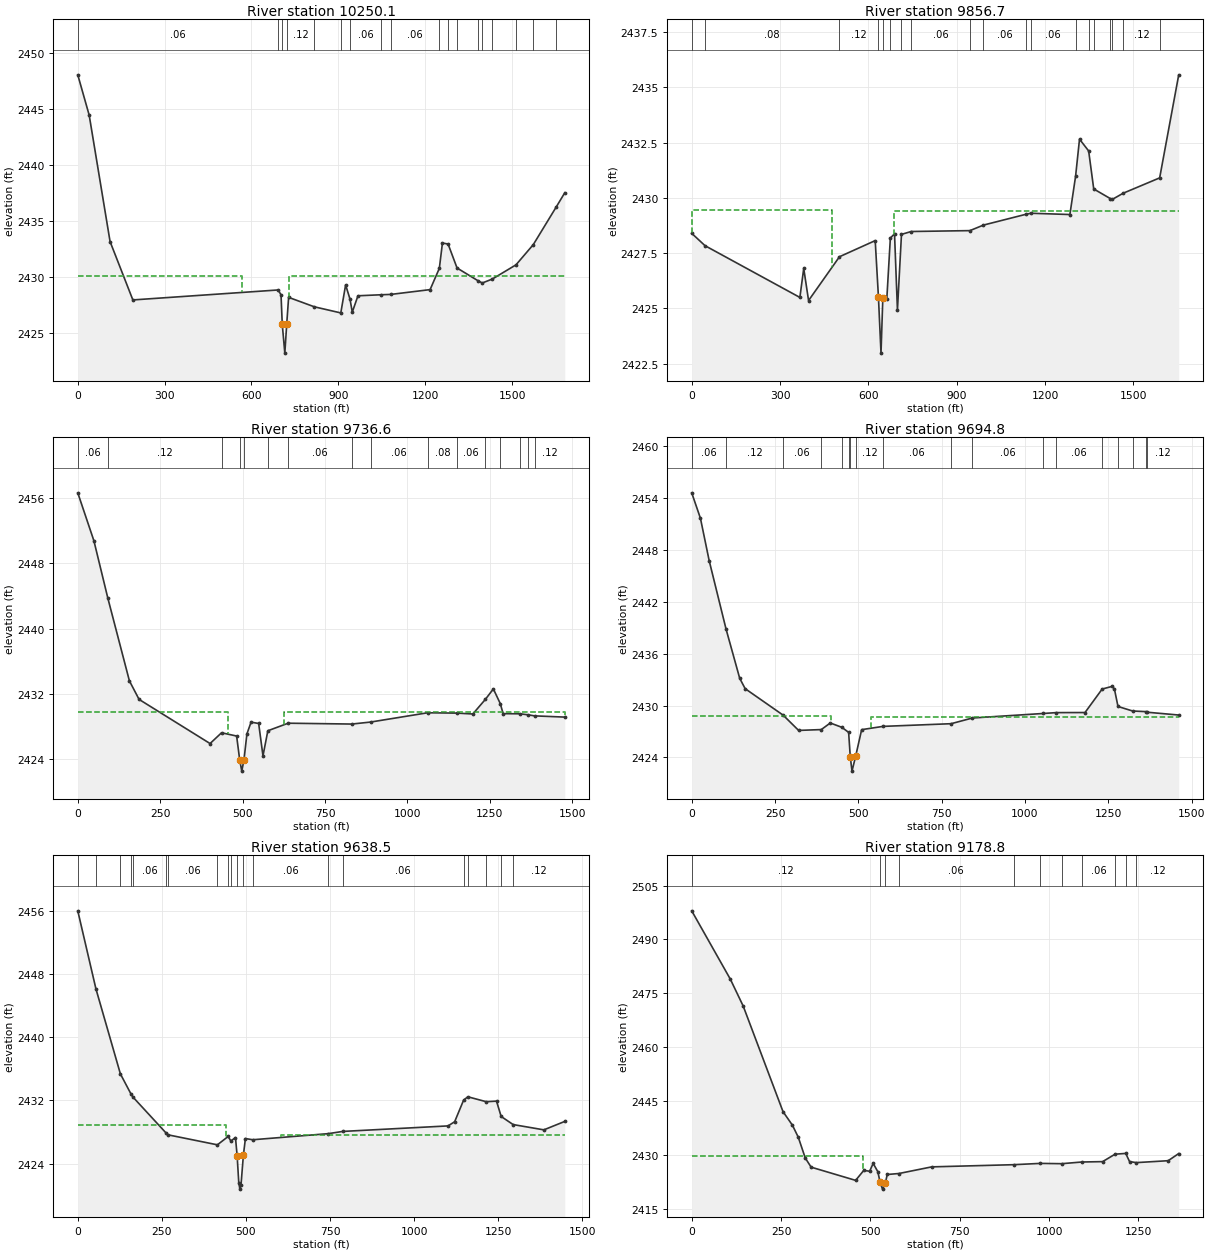
Type RM Length L Ch R = 1 ,10250.1 ,399.5,393.4,384.2
XS GIS Cut Line= 3
      2016221.46      307430.236      2015184.35      307773.737
     2015007.267      308336.237
#Sta/Elev= 30
       0 2448.05    39.4 2444.46   111.6 2433.19   190.3 2427.99  692.232428.879
   702.1 2428.44  706.332425.816   715.2 2423.25   721.8 2425.85   728.3 2428.22
  817.222427.377  908.532426.833   925.2 2429.33  940.362428.062   948.2  2426.9
   967.8 2428.36 1048.112428.452 1081.262428.482    1217 2428.91  1248.92430.803
  1259.6 2433.06 1279.132432.973 1310.092430.836 1381.782429.712 1397.162429.501
 1431.682429.849 1513.662431.117 1573.512432.923 1652.312436.258  1682.2 2437.54
#Mann= 18 ,-1 , 0
       0     .06       0  692.23     .12       0  706.33    .045       0
   721.8     .12       0  817.22     .06       0  908.53    .016       0
  940.36     .06       0 1048.11    .016       0 1081.26     .06       0
  1248.9    .016       0 1279.13     .08       0 1310.09     .06       0
 1381.78     .08       0 1397.16     .06       0 1431.68     .12       0
 1513.66     .06       0 1573.51     .12       0 1652.31     .06       0
#XS Ineff= 2 , 0
          566.56 2430.14  730.03         2430.08
Permanent Ineff=
       F       F
Bank Sta=706.33,721.8
XS Rating Curve= 0 ,0
Exp/Cntr=0.3,0.1

Type RM Length L Ch R = 1 ,9856.7  ,150.5,120.2,85.3
XS GIS Cut Line= 3
     2015844.477      306958.228     2015245.519      307411.353
      2014977.29      308273.332
#Sta/Elev= 30
       0  2428.4   45.152427.841   367.3  2425.5   380.4 2426.81   396.8 2425.36
  501.772427.341   623.1 2428.07     634 2425.54   642.8 2422.98     649 2425.48
   662.5 2425.43  674.542428.184   688.7 2428.38   698.6 2424.93  712.312428.352
  745.472428.482  944.712428.522  990.792428.773 1133.532429.256 1151.682429.308
  1284.2 2429.25 1303.572430.982  1316.9 2432.66 1347.922432.126 1365.172430.407
  1421.52429.971 1428.222429.935 1465.342430.215 1589.062430.908  1653.8 2435.57
#Mann= 19 ,-1 , 0
       0     .12       0   45.15     .08       0  501.77     .12       0
     634    .045       0     649     .12       0  674.54    .016       0
  712.31     .12       0  745.47     .06       0  944.71    .016       0
  990.79     .06       0 1133.53     .08       0 1151.68     .06       0
 1303.57    .016       0 1347.92     .08       0 1365.17     .06       0
  1421.5     .12       0 1428.22     .06       0 1465.34     .12       0
 1589.06     .06       0
#XS Ineff= 2 , 0
          475.54 2429.45  685.45          2429.4
Permanent Ineff=
       F       F
Bank Sta=634,649
XS Rating Curve= 0 ,0
Exp/Cntr=0.3,0.1

Type RM Length L Ch R = 1 ,9736.6  ,41.7,41.7,44.4
XS GIS Cut Line= 4
     2015408.117      306785.811     2015253.679      307218.991
      2015279.43      307275.888     2014964.269      308176.978
#Sta/Elev= 30
       0 2456.65    48.9 2450.78   91.282443.734   156.6 2433.61   185.9 2431.34
   401.2 2425.93  436.07 2427.25   481.8 2426.85   491.1 2423.93   497.4 2422.55
  504.082423.937     513 2427.11   525.6 2428.55   548.6 2428.39   561.7 2424.42
  576.472427.497  638.132428.422  830.952428.318  887.832428.561 1060.982429.699
 1150.852429.659  1198.1 2429.55 1236.142431.341  1260.4 2432.62 1281.432430.822
    1290 2429.59 1340.972429.574 1365.482429.454 1385.192429.321    1477 2429.17
#Mann= 16 ,-1 , 0
       0     .06       0   91.28     .12       0  436.07    .016       0
   491.1    .045       0  504.08    .016       0  576.47     .12       0
  638.13     .06       0  830.95    .016       0  887.83     .06       0
 1060.98     .08       0 1150.85     .06       0 1236.14    .016       0
 1281.43     .06       0 1340.97     .12       0 1365.48     .06       0
 1385.19     .12       0
#XS Ineff= 2 , 0
          455.73  2429.8   625.8          2429.8
Permanent Ineff=
       F       F
Bank Sta=491.1,504.08
XS Rating Curve= 0 ,0
Exp/Cntr=0.3,0.1

Type RM Length L Ch R = 1 ,9694.8  ,55.2,56.3,57.2
XS GIS Cut Line= 4
     2015369.228        306799.7     2015215.484      307231.491
     2015241.179      307287.047     2014933.019      308176.978
#Sta/Elev= 30
       0 2454.61    26.2 2451.66    52.4 2446.76  103.062438.842     144 2433.15
   160.4 2431.95   274.42428.884   320.8 2427.12  388.822427.218   415.8 2427.98
  450.342427.481  470.842426.896   475.72424.099   480.9 2422.41   492.1 2424.17
   509.9 2427.21  574.162427.587  778.342427.897  842.232428.557 1055.532429.082
 1093.97 2429.18  1180.1 2429.19 1231.542431.907  1261.9 2432.22  1268.4  2431.9
 1279.06 2429.89 1322.932429.367 1361.992429.295 1367.122429.224  1461.3  2428.9
#Mann= 18 ,-1 , 0
       0     .06       0  103.06     .12       0   274.4     .06       0
  388.82    .016       0  450.34     .06       0  470.84     .12       0
   475.7    .045       0   492.1     .12       0  574.16     .06       0
  778.34    .016       0  842.23     .06       0 1055.53     .08       0
 1093.97     .06       0 1231.54    .016       0 1279.06     .06       0
 1322.93     .12       0 1361.99     .06       0 1367.12     .12       0
#XS Ineff= 2 , 0
           419.4 2428.81  538.29         2428.69
Permanent Ineff=
       F       F
Bank Sta=475.7,492.1
XS Rating Curve= 0 ,0
Exp/Cntr=0.3,0.1

Type RM Length L Ch R = 1 ,9638.5  ,451.8,459.7,462.1
XS GIS Cut Line= 3
     2014987.707      306830.623     2015193.436      307320.207
     2014904.373      308189.998
#Sta/Elev= 30
       0 2456.03      542446.142  126.732435.367  158.77 2432.78  164.052432.432
  262.662427.873  267.442427.657  415.082426.383  447.122427.446  454.852426.871
   468.8  2427.3   473.7    2425   478.6 2421.57   481.9 2420.77   485.2  2421.3
  492.33 2425.09   498.3 2427.18  520.082427.026  744.412427.798  787.572428.081
  1100.6 2428.78  1120.3 2429.31 1146.882432.046  1159.5 2432.47 1214.182431.844
  1244.7 2431.92  1258.52429.976 1293.982428.951  1385.4 2428.28  1447.6 2429.35
#Mann= 20 ,-1 , 0
       0     .12       0      54     .08       0  126.73    .016       0
  158.77     .08       0  164.05     .06       0  262.66     .08       0
  267.44     .06       0  415.08     .12       0  447.12     .06       0
  454.85     .12       0   473.7    .045       0  492.33     .12       0
  520.08     .06       0  744.41    .016       0  787.57     .06       0
 1146.88     .08       0  1159.5     .06       0 1214.18    .016       0
  1258.5     .06       0 1293.98     .12       0
#XS Ineff= 2 , 0
          439.22 2428.85   604.9         2427.69
Permanent Ineff=
       F       F
Bank Sta=473.7,492.33
XS Rating Curve= 0 ,0
Exp/Cntr=0.3,0.1

Type RM Length L Ch R = 1 ,9178.8  ,276.2,276.8,275.9
XS GIS Cut Line= 2
     2014650.698      306839.281     2014854.489      308186.931
#Sta/Elev= 30
       0 2497.95   108.1 2478.91   144.2 2471.39   255.6 2441.99   281.8 2438.24
   298.2 2434.89   317.8 2429.09   334.2 2426.54   458.7 2422.86   481.6 2425.64
     498  2425.4   507.8 2427.59   520.9 2425.28   527.1 2422.39     534 2420.42
   542.1 2422.17   547.2  2424.5  579.722424.767   671.7 2426.62  901.122427.228
  975.73 2427.59 1035.482427.506  1092.22427.978    1150 2428.08 1184.842430.156
 1214.722430.366  1225.4 2428.09 1244.592427.806  1333.5 2428.34    1363 2430.33
#Mann= 11 ,-1 , 0
       0     .12       0   527.1    .045       0   542.1     .12       0
  579.72     .06       0  901.12     .08       0  975.73     .06       0
 1035.48     .08       0  1092.2     .06       0 1184.84    .016       0
 1214.72     .06       0 1244.59     .12       0
#XS Ineff= 2 , 0
          479.67 2429.59
Permanent Ineff=
       F       F
Bank Sta=527.1,542.1
XS Rating Curve= 0 ,0
Exp/Cntr=0.3,0.1

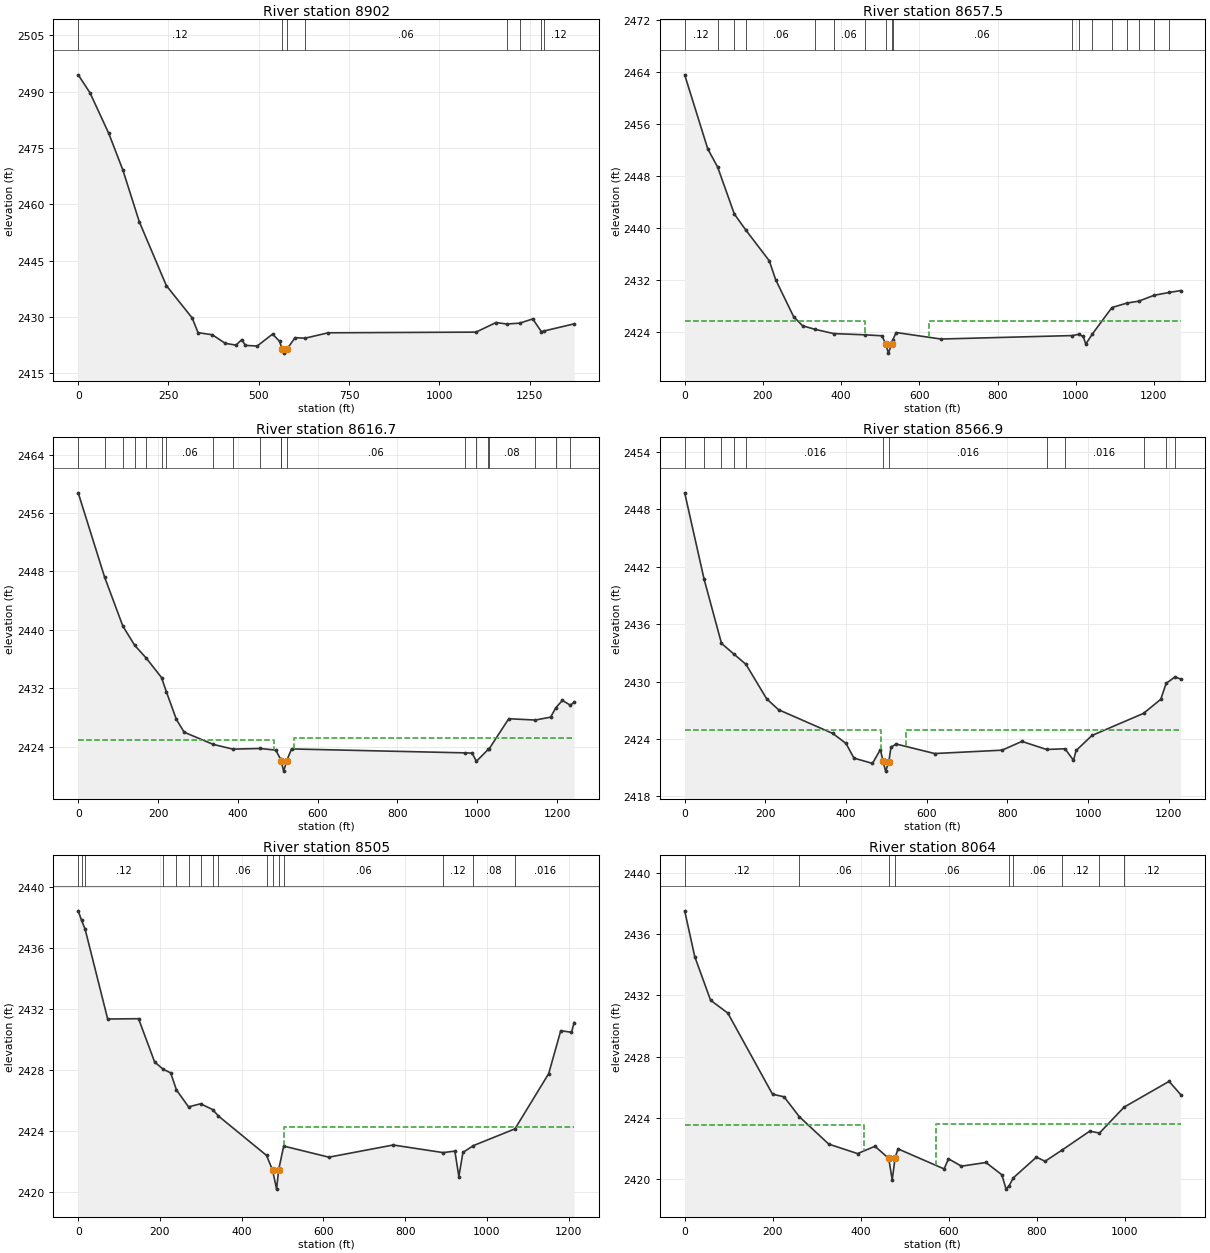
Type RM Length L Ch R = 1 ,8902    ,240.8,244.5,247.5
XS GIS Cut Line= 3
     2014496.153      306866.879     2014423.786      307173.997
      2014586.98      308219.136
#Sta/Elev= 30
       0 2494.47    32.5 2489.71    84.6 2478.88   123.6 2469.15   169.2 2455.37
     244 2438.39   315.5 2429.78   331.9 2425.86   371.2  2425.3   407.2 2423.02
   436.7 2422.54   453.1 2424.01   462.9 2422.47   495.6  2422.3   538.2 2425.48
   557.9 2423.52   564.4 2421.45     571 2420.41  578.142421.477   600.4 2424.52
  628.532424.391   692.2 2425.82  1101.5    2426  1157.2 2428.56 1185.97 2428.16
 1222.272428.384  1258.7 2429.51 1282.762426.097 1289.092426.285  1373.3  2428.2
#Mann= 8 ,-1 , 0
       0     .12       0   564.4    .045       0  578.14     .12       0
  628.53     .06       0 1185.97     .08       0 1222.27    .016       0
 1282.76     .06       0 1289.09     .12       0
Bank Sta=564.4,578.14
XS Rating Curve= 0 ,0
Exp/Cntr=0.3,0.1

Type RM Length L Ch R = 1 ,8657.5  ,40.9,40.8,40.9
XS GIS Cut Line= 2
     2014219.824      306968.153     2014237.967      308236.179
#Sta/Elev= 30
       0 2463.54      59 2452.15   84.352449.339  126.992442.123  156.532439.643
   216.3 2434.93   232.7 2432.02   278.5 2426.34   301.5 2424.93  333.582424.374
  381.352423.726  459.86 2423.54   504.6 2423.39   514.5 2422.06     521 2420.72
  528.942422.061  531.642422.671   540.7 2423.89   655.4 2422.89  989.55 2423.42
 1007.29  2423.6  1019.1 2423.31  1025.7 2422.11 1042.752423.685 1092.582427.737
 1131.372428.428 1160.912428.711 1200.332429.622 1238.812430.052  1268.2 2430.34
#Mann= 18 ,-1 , 0
       0     .12       0   84.35     .08       0  126.99     .12       0
  156.53     .06       0  333.58    .016       0  381.35     .06       0
  459.86     .07       0   514.5    .045       0  528.94     .07       0
  531.64     .06       0  989.55     .12       0 1007.29     .06       0
 1042.75     .12       0 1092.58     .08       0 1131.37     .12       0
 1160.91     .06       0 1200.33    .016       0 1238.81     .12       0
#XS Ineff= 2 , 0
          462.33 2425.74  625.59         2425.74
Permanent Ineff=
       F       F
Bank Sta=514.5,528.94
XS Rating Curve= 0 ,0
Exp/Cntr=0.3,0.1

Type RM Length L Ch R = 1 ,8616.7  ,50,49.8,49.7
XS GIS Cut Line= 2
     2014180.702      306983.269     2014198.884      308226.058
#Sta/Elev= 30
       0 2458.77   66.092447.232  111.872440.513  141.422437.887  170.962436.094
  208.82 2433.46  221.212431.474     246 2427.73   265.6 2425.97  338.172424.309
  387.392423.656  455.312423.742   495.2 2423.52  507.342422.254   508.3 2422.05
   514.9 2420.64   522.6 2422.08   534.6 2423.68  968.592423.143   987.1 2423.11
     9982421.988 1027.642423.625 1029.832423.691    1079 2427.82  1145.8 2427.64
  1183.9 2428.04 1197.072429.331  1213.4 2430.33  1233.42429.674  1242.9 2430.07
#Mann= 20 ,-1 , 0
       0     .12       0   66.09     .06       0  111.87    .016       0
  141.42     .12       0  170.96     .06       0  208.82     .12       0
  221.21     .06       0  338.17    .016       0  387.39     .06       0
  455.31     .07       0  507.34     .06       0   508.3    .045       0
   522.6     .06       0  968.59     .12       0     998     .06       0
 1027.64     .12       0 1029.83     .08       0  1145.8     .06       0
 1197.07    .016       0  1233.4     .12       0
#XS Ineff= 2 , 0
          491.23 2424.93   541.8         2425.14
Permanent Ineff=
       F       F
Bank Sta=508.3,522.6
XS Rating Curve= 0 ,0
Exp/Cntr=0.3,0.1

Type RM Length L Ch R = 1 ,8566.9  ,62.7,61.9,61.1
XS GIS Cut Line= 2
     2014131.425      307002.307     2014149.404      308231.266
#Sta/Elev= 30
       0 2449.74   48.092440.715   91.232433.997  122.372432.866  151.922431.804
   203.2  2428.2   232.7 2427.06   367.1 2424.58   399.9 2423.53   419.5    2422
   465.4 2421.45   485.1  2422.9   491.6 2421.66   498.2 2420.64   505.92421.635
   511.3 2423.15   524.4 2423.47   619.5 2422.48   786.6 2422.83   835.8 2423.75
  896.862422.904  942.612422.978   963.6 2421.77   970.2  2422.8  1009.5 2424.37
 1137.142426.679  1179.9 2428.15  1193.12429.804 1215.38  2430.5  1229.1 2430.26
#Mann= 12 ,-1 , 0
       0     .12       0   48.09     .06       0   91.23     .12       0
  122.37     .06       0  151.92    .016       0   491.6    .045       0
   505.9    .016       0  896.86     .08       0  942.61    .016       0
 1137.14     .06       0  1193.1    .016       0 1215.38     .08       0
#XS Ineff= 2 , 0
          485.45 2424.97  547.57         2424.92
Permanent Ineff=
       F       F
Bank Sta=491.6,505.9
XS Rating Curve= 0 ,0
Exp/Cntr=0.3,0.1

Type RM Length L Ch R = 1 ,8505    ,439.1,441,439.7
XS GIS Cut Line= 2
     2014053.691      307032.341     2014115.571      308243.991
#Sta/Elev= 30
       0 2438.45    8.362437.815      172437.232    72.1 2431.34   147.6 2431.36
   186.9 2428.52  207.622428.042   226.2  2427.8  240.332426.677   269.92425.566
  299.48 2425.77  329.062425.385  342.76 2424.97  460.732422.374   475.4 2421.41
   485.3 2420.16  490.212421.417  502.71 2422.99   613.2 2422.26   770.6 2423.06
  892.75 2422.56   921.4 2422.66   931.2 2420.98   941.1 2422.57  966.472423.018
 1068.462424.122  1150.9 2427.75  1180.4 2430.57  1206.7 2430.47  1213.2 2431.11
#Mann= 16 ,-1 , 0
       0     .12       0    8.36     .06       0      17     .12       0
  207.62    .016       0  240.33     .08       0   269.9     .12       0
  299.48     .08       0  329.06     .12       0  342.76     .06       0
  460.73     .12       0   475.4    .045       0  490.21     .12       0
  502.71     .06       0  892.75     .12       0  966.47     .08       0
 1068.46    .016       0
#XS Ineff= 2 , 0
                          504.23         2424.26
Permanent Ineff=
       F       F
Bank Sta=475.4,490.21
XS Rating Curve= 0 ,0
Exp/Cntr=0.3,0.1

Type RM Length L Ch R = 1 ,8064    ,761,762.6,760
XS GIS Cut Line= 3
     2013573.722      307194.417     2013643.957      307262.915
     2013683.019      308291.561
#Sta/Elev= 30
       0 2437.52    22.9 2434.53    58.9 2431.68    98.1 2430.84   199.7 2425.54
     226 2425.37  260.652424.071   327.6 2422.28   393.2 2421.66   432.5 2422.14
   463.9 2421.35   471.8 2419.94   478.4 2421.38     485 2421.97   589.8 2420.66
   599.7 2421.32   629.2 2420.84   684.9 2421.08     721 2420.28   730.8 2419.34
  737.782419.574  747.392420.085   799.7 2421.43   819.3 2421.16  857.38 2421.88
     921 2423.13  942.942423.002  998.872424.694  1101.3 2426.38  1127.5 2425.52
#Mann= 9 ,-1 , 0
       0     .12       0  260.65     .06       0   463.9    .045       0
   478.4     .06       0  737.78     .08       0  747.39     .06       0
  857.38     .12       0  942.94     .06       0  998.87     .12       0
#XS Ineff= 2 , 0
          407.43 2423.53  572.14         2423.61
Permanent Ineff=
       F       F
Bank Sta=463.9,478.4
XS Rating Curve= 0 ,0
Exp/Cntr=0.3,0.1

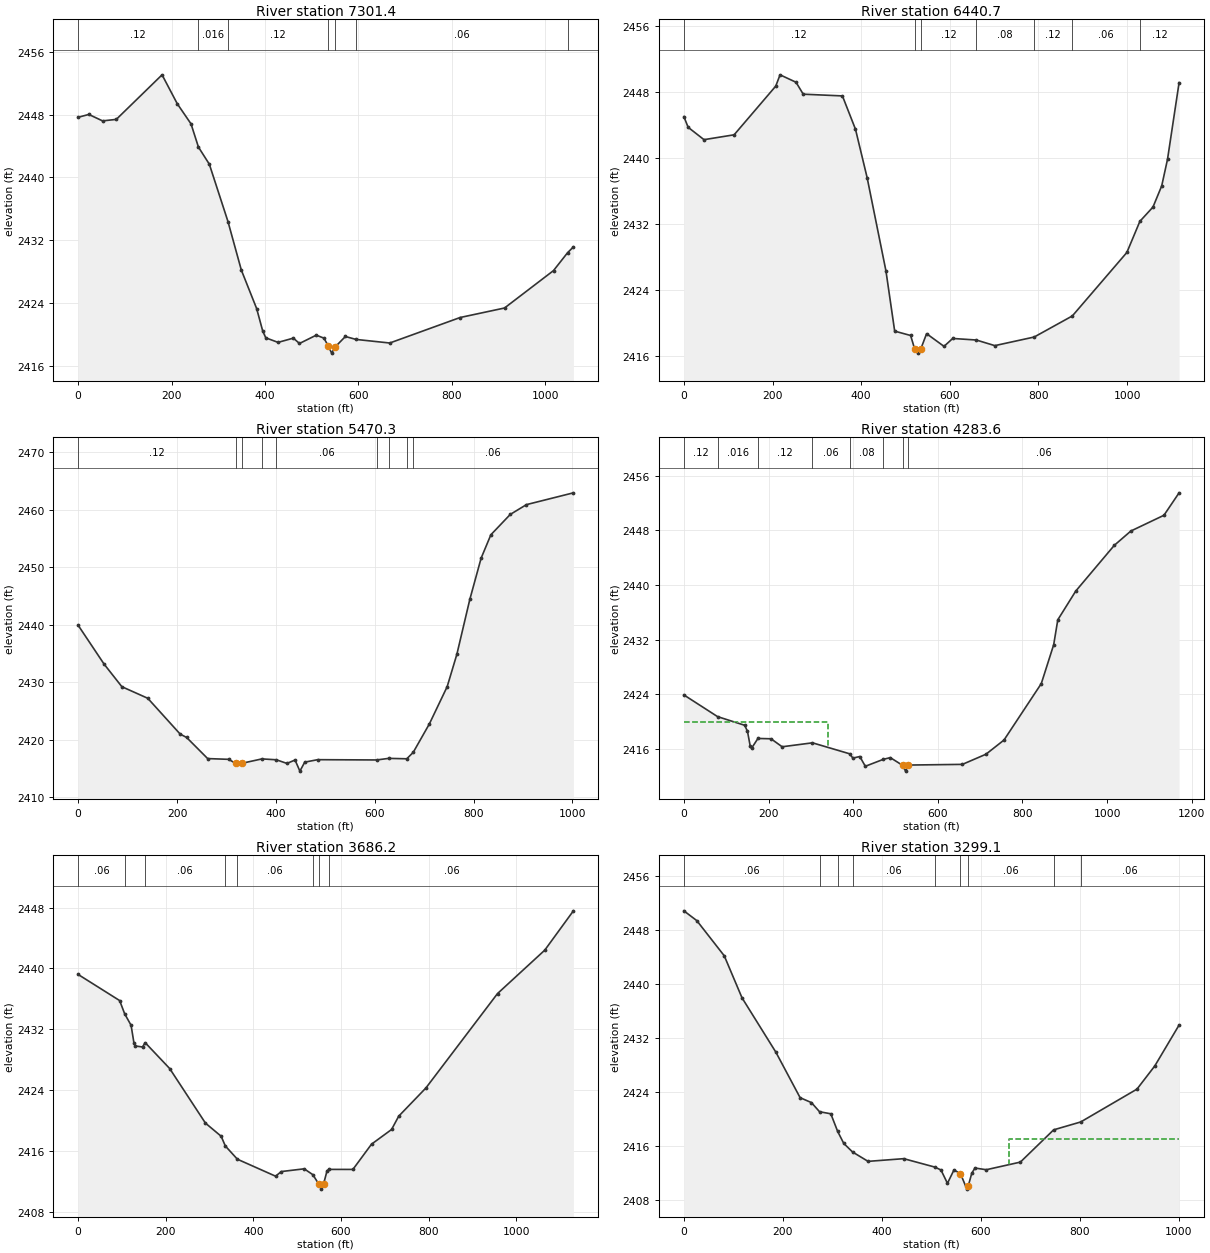
Type RM Length L Ch R = 1 ,7301.4  ,697.2,860.7,709.3
XS GIS Cut Line= 3
     2012882.882      307370.757     2012961.665      307717.776
     2013022.911      308419.555
#Sta/Elev= 30
       0 2447.66    22.8 2448.02    52.2  2447.2    81.6 2447.39   179.6 2453.07
   212.2 2449.38   241.6 2446.82  257.452443.864   280.8 2441.68  320.722434.371
   349.3 2428.19   382.1 2423.28   395.2  2420.4   401.7 2419.55   427.9 2418.97
   460.7 2419.51   473.8 2418.83   509.8 2419.89   526.2 2419.51   535.9 2418.46
   542.6  2417.6   550.9 2418.43   572.1 2419.72  594.832419.346   667.1 2418.89
   817.8 2422.14   912.8 2423.35  1017.7 2428.12 1047.852430.399  1060.3 2431.14
#Mann= 7 ,-1 , 0
       0     .12       0  257.45    .016       0  320.72     .12       0
   535.9    .045       0   550.9     .12       0  594.83     .06       0
 1047.85     .08       0
Bank Sta=535.9,550.9
XS Rating Curve= 0 ,0
Exp/Cntr=0.3,0.1

Type RM Length L Ch R = 1 ,6440.7  ,960.4,970.5,788
XS GIS Cut Line= 3
     2012829.044       307374.02     2012821.138      307600.647
     2012132.973      308165.788
#Sta/Elev= 30
       0 2445.05     9.7 2443.75    45.4 2442.25   113.4 2442.84   207.3 2448.75
     217 2450.12     253 2449.22   269.3 2447.77   357.7 2447.56   387.2 2443.51
   413.4 2437.65   455.9 2426.32   475.6 2419.01   511.6 2418.48   520.72416.833
     528 2416.34   534.5 2416.85   547.6  2418.7   586.9 2417.16   606.5 2418.12
  659.762417.931   701.5 2417.25   790.32418.294   876.42420.855   999.4 2428.56
 1028.752432.336  1058.3 2434.07    1078 2436.64  1091.1 2439.87  1117.2 2449.17
#Mann= 7 ,-1 , 0
       0     .12       0   520.7    .045       0   534.5     .12       0
  659.76     .08       0   790.3     .12       0   876.4     .06       0
 1028.75     .12       0
Bank Sta=520.7,534.5
XS Rating Curve= 0 ,0
Exp/Cntr=0.3,0.1

Type RM Length L Ch R = 1 ,5470.3  ,944.6,1186.7,1133.8
XS GIS Cut Line= 2
     2012429.108      307193.524     2011718.708      307900.126
#Sta/Elev= 30
       0 2439.92    52.4 2433.18    88.4 2429.25   140.8 2427.24   206.3 2421.02
   219.4 2420.43     262 2416.76   304.5 2416.63  318.642415.918   331.6 2415.95
   371.82416.704   400.92416.552   422.4 2415.92   438.8 2416.51   448.6 2414.58
   458.4 2416.14   484.6 2416.57   603.92416.521   628.42416.797  664.862416.724
  677.89 2417.84   710.6 2422.79   746.6 2429.26   766.2 2434.88   792.4 2444.42
   815.3 2451.59     835 2455.65   874.3 2459.19     907 2460.89    1002 2462.94
#Mann= 9 ,-1 , 0
       0     .12       0  318.64    .045       0   331.6     .12       0
   371.8     .08       0   400.9     .06       0   603.9     .08       0
   628.4     .06       0  664.86     .08       0  677.89     .06       0
Bank Sta=318.64,331.6
XS Rating Curve= 0 ,0
Exp/Cntr=0.3,0.1

Type RM Length L Ch R = 1 ,4283.6  ,466.6,597.3,437
XS GIS Cut Line= 4
       2011708.8      306697.568     2011660.677      306775.128
     2011623.098      307462.282     2011685.623      307847.985
#Sta/Elev= 30
       0 2423.88   79.682420.698   143.7 2419.43   150.3 2418.55   156.8 2416.38
   160.1 2416.08  175.07  2417.5     206 2417.45   232.2 2416.28  303.952416.858
  392.032415.245   399.3 2414.62   415.7 2414.85   428.8 2413.42  470.892414.428
   487.8 2414.69   517.3 2413.54   523.8 2412.71   530.4  2413.6   658.2  2413.7
   713.9 2415.19   756.5 2417.27   844.6 2425.54   873.9 2431.24   883.6 2434.89
     926  2439.1  1017.2 2445.81  1056.2  2447.9  1134.4 2450.21  1170.2  2453.5
#Mann= 8 ,-1 , 0
       0     .12       0   79.68    .016       0  175.07     .12       0
  303.95     .06       0  392.03     .08       0  470.89     .06       0
   517.3    .045       0   530.4     .06       0
#XS Ineff= 2 , 0
          340.56 2419.88
Permanent Ineff=
       F       F
Bank Sta=517.3,530.4
XS Rating Curve= 0 ,0
Exp/Cntr=0.3,0.1

Type RM Length L Ch R = 1 ,3686.2  ,360.1,387.1,343.1
XS GIS Cut Line= 3
     2011036.751       306738.05     2011247.267      306956.853
     2011387.892      307771.957
#Sta/Elev= 30
       0 2439.21    94.7 2435.78  106.222434.033   120.8 2432.53   127.3 2430.23
   130.6 2429.81   146.9 2429.68  152.972430.249     209 2426.84   290.6 2419.67
   326.5 2417.94     3362416.664  363.592414.921   450.8 2412.69   463.8  2413.3
   516.1 2413.66   535.8 2412.89   548.8 2411.71   555.4 2410.99  560.592411.726
   568.4 2413.43  573.342413.584   627.3 2413.58   669.8  2416.9   715.6 2418.83
   731.9 2420.58     794 2424.29   957.5  2436.7  1065.4 2442.41  1130.8 2447.58
#Mann= 8 ,-1 , 0
       0     .06       0  106.22    .016       0  152.97     .06       0
     336     .12       0  363.59     .06       0   535.8    .045       0
   548.8     .08       0  573.34     .06       0
Bank Sta=548.8,560.59
XS Rating Curve= 0 ,0
Exp/Cntr=0.3,0.1

Type RM Length L Ch R = 1 ,3299.1  ,340.5,371.5,385.7
XS GIS Cut Line= 3
     2010853.736      306793.639     2011045.531      307028.815
     2011175.739      307713.711
#Sta/Elev= 30
       0 2450.88    26.1 2449.43    81.6 2444.21   117.5 2437.97     186 2429.89
   234.9 2423.15   257.8 2422.42  274.142421.065   296.9 2420.76   310.82418.138
   323.1 2416.36  340.87 2415.09   372.2  2413.7   444.2  2414.1  507.032412.853
   519.5 2412.42   532.6 2410.44   545.7 2412.42   558.8 2411.89   571.9 2409.58
  574.622410.039   581.7 2411.94   588.2 2412.71   611.1 2412.46   679.9 2413.59
  747.152418.379  801.792419.545   915.5 2424.42   951.5 2427.86  1000.6 2433.93
#Mann= 9 ,-1 , 0
       0     .06       0  274.14    .016       0   310.8     .08       0
  340.87     .06       0  507.03     .12       0   558.8    .045       0
  574.62     .06       0  747.15    .016       0  801.79     .06       0
#XS Ineff= 2 , 0
                          657.59         2417.03
Permanent Ineff=
       F       F
Bank Sta=558.8,574.62
XS Rating Curve= 0 ,0
Exp/Cntr=0.3,0.1

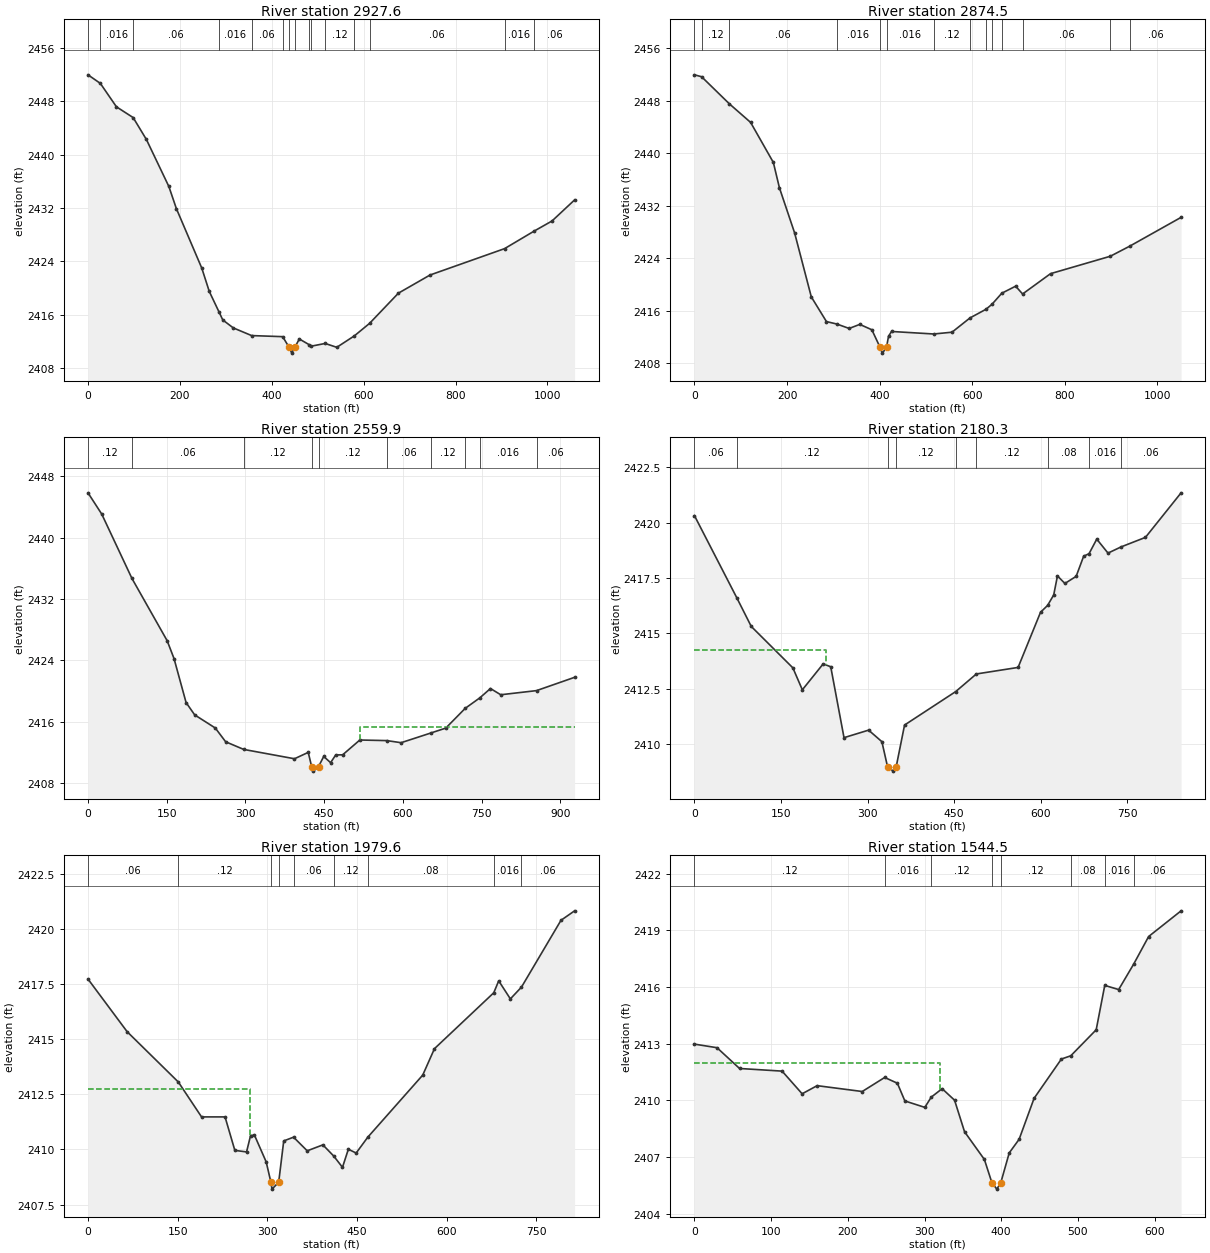
Type RM Length L Ch R = 1 ,2927.6  ,53,53.1,52.9
XS GIS Cut Line= 4
     2010794.663      306815.707     2010891.017      307109.978
     2010766.017      307422.478     2011042.058       307729.77
#Sta/Elev= 30
       0 2451.94   26.862450.659    61.9 2447.15   98.332445.535   127.1 2442.26
     176 2435.22   192.3 2431.92   247.7 2422.99     264  2419.5  285.662416.362
   293.4 2415.23   316.2 2414.04  356.192412.888  423.752412.726   437.1 2411.21
   443.6 2410.26   450.2 2411.13     460 2412.38  480.982411.543  484.492411.282
   516.32411.707   541.6 2411.13  579.93 2412.85  612.972414.719   675.7 2419.24
   744.6 2421.96  906.812425.909  971.732428.558  1010.1 2430.05  1059.3 2433.21
#Mann= 15 ,-1 , 0
       0     .06       0   26.86    .016       0   98.33     .06       0
  285.66    .016       0  356.19     .06       0  423.75     .08       0
   437.1    .045       0   450.2     .08       0  480.98    .016       0
  484.49     .08       0   516.3     .12       0  579.93     .08       0
  612.97     .06       0  906.81    .016       0  971.73     .06       0
Bank Sta=437.1,450.2
XS Rating Curve= 0 ,0
Exp/Cntr=0.3,0.1

Type RM Length L Ch R = 1 ,2874.5  ,314.3,314.5,298.2
XS GIS Cut Line= 4
     2010737.295      306831.242     2010831.121      307117.791
     2010706.121      307430.291     2010982.163      307737.582
#Sta/Elev= 30
       0 2451.97   15.39 2451.68   75.632447.535   121.3 2444.72   170.4 2438.62
   183.5 2434.76   216.3 2427.89   252.4 2418.13   285.1 2414.37   307.92413.986
   334.2 2413.32   357.1 2413.94   383.2 2413.12  400.472410.512   406.1 2409.56
  414.872410.457   419.2 2412.12   425.7 2412.86  516.962412.476   556.4 2412.75
   595.22414.924  629.722416.242  642.752417.008  663.972418.693   693.8 2419.76
  708.842418.572   769.2 2421.67  898.252424.321  940.512425.869  1051.2 2430.25
#Mann= 14 ,-1 , 0
       0    .016       0   15.39     .12       0   75.63     .06       0
   307.9    .016       0  400.47    .045       0  414.87    .016       0
  516.96     .12       0   595.2     .08       0  629.72     .06       0
  642.75     .08       0  663.97    .016       0  708.84     .06       0
  898.25    .016       0  940.51     .06       0
Bank Sta=400.47,414.87
XS Rating Curve= 0 ,0
Exp/Cntr=0.3,0.1

Type RM Length L Ch R = 1 ,2559.9  ,417.8,379.7,304.1
XS GIS Cut Line= 3
     2010672.267      306883.416     2010575.913      307435.499
     2010838.933      307690.707
#Sta/Elev= 30
       0 2445.82    26.2 2443.05   83.762434.671   150.8 2426.57   163.9 2424.24
   186.8 2418.53   203.2 2416.92   242.5 2415.21   262.2 2413.42  296.612412.425
   393.3 2411.21   419.5 2412.04   426.1 2410.16   429.3  2409.6   439.2  2410.2
     449 2411.51   462.1  2410.7   471.9 2411.71     485 2411.72   517.8 2413.65
  569.162413.573   596.4  2413.3     6532414.561   681.5  2415.2  718.572417.775
  746.192419.128   766.6 2420.35   786.2 2419.54  854.342420.078   926.9 2421.81
#Mann= 10 ,-1 , 0
       0     .12       0   83.76     .06       0  296.61     .12       0
   426.1    .045       0   439.2     .12       0  569.16     .06       0
     653     .12       0  718.57     .08       0  746.19    .016       0
  854.34     .06       0
#XS Ineff= 2 , 0
                          518.06         2415.34
Permanent Ineff=
       F       F
Bank Sta=426.1,439.2
XS Rating Curve= 0 ,0
Exp/Cntr=0.3,0.1

Type RM Length L Ch R = 1 ,2180.3  ,210.5,200.7,188.8
XS GIS Cut Line= 3
     2010099.703      307306.051     2010607.498       307519.86
     2010831.457       307707.36
#Sta/Elev= 30
       0 2420.31   73.282416.606    98.4 2415.31   170.5 2413.44   186.9 2412.45
     223 2413.62   236.1 2413.49   259.1 2410.29   301.7 2410.63   324.7 2410.11
   334.5 2408.98   344.4 2408.78   349.42408.962     364 2410.86  452.61 2412.37
  488.392413.165   560.7 2413.46   599.6 2415.95   611.82416.258   622.4 2416.73
   628.9 2417.59   641.8 2417.25   661.3 2417.57   674.3 2418.48  683.652418.594
     697 2419.25   716.5 2418.62   739.2  2418.9   781.4 2419.33   843.1 2421.34
#Mann= 9 ,-1 , 0
       0     .06       0   73.28     .12       0   334.5    .045       0
   349.4     .12       0  452.61     .06       0  488.39     .12       0
   611.8     .08       0  683.65    .016       0   739.2     .06       0
#XS Ineff= 2 , 0
          228.07 2414.24
Permanent Ineff=
       F       F
Bank Sta=334.5,349.4
XS Rating Curve= 0 ,0
Exp/Cntr=0.3,0.1

Type RM Length L Ch R = 1 ,1979.6  ,449.5,435.1,418.7
XS GIS Cut Line= 3
     2010047.828       307646.54     2010622.788       307604.77
     2010823.308      307732.374
#Sta/Elev= 30
       0 2417.74    65.5 2415.35  151.152413.065     190 2411.48   229.3 2411.48
   245.7 2409.96   265.3 2409.89   271.9 2410.62   278.4 2410.66   298.1 2409.44
     306 2408.52   307.9  2408.2  319.072408.515   327.5 2410.39  343.952410.559
   366.8 2409.94     393 2410.21  411.112409.703   425.8 2409.19   435.6 2410.01
   448.7 2409.84  468.052410.556   560.1 2413.38   579.7 2414.58  678.932417.119
   687.2 2417.66   706.7 2416.84  725.272417.375   791.4 2420.41   814.2 2420.84
#Mann= 9 ,-1 , 0
       0     .06       0  151.15     .12       0     306    .045       0
  319.07     .12       0  343.95     .06       0  411.11     .12       0
  468.05     .08       0  678.93    .016       0  725.27     .06       0
#XS Ineff= 2 , 0
          271.41 2412.73
Permanent Ineff=
       F       F
Bank Sta=306,319.07
XS Rating Curve= 0 ,0
Exp/Cntr=0.3,0.1

Type RM Length L Ch R = 1 ,1544.5  ,108.2,121.7,134.4
XS GIS Cut Line= 4
     2010234.767      307875.603     2010521.225      307852.166
     2010677.475      307706.332     2010802.475      307753.207
#Sta/Elev= 30
       0 2412.98    29.4 2412.79    58.8 2411.69   114.3 2411.55   140.4 2410.35
     160 2410.78   218.8 2410.47  248.062411.214   264.6 2410.91   274.4 2409.97
   300.4 2409.63  308.812410.173     323 2410.62   339.2 2410.01   352.2 2408.34
   378.1 2406.87   387.8 2405.65   394.3  2405.3  399.492405.641   410.5 2407.22
   423.4 2407.94   442.9 2410.11   478.5 2412.19  490.752412.362   523.9 2413.74
  535.06 2416.09   553.2 2415.87   572.8 2417.22   592.3 2418.68   634.6 2420.04
#Mann= 8 ,-1 , 0
       0     .12       0  248.06    .016       0  308.81     .12       0
   387.8    .045       0  399.49     .12       0  490.75     .08       0
  535.06    .016       0   572.8     .06       0
#XS Ineff= 2 , 0
          320.74 2411.97
Permanent Ineff=
       F       F
Bank Sta=387.8,399.49
XS Rating Curve= 0 ,0
Exp/Cntr=0.3,0.1