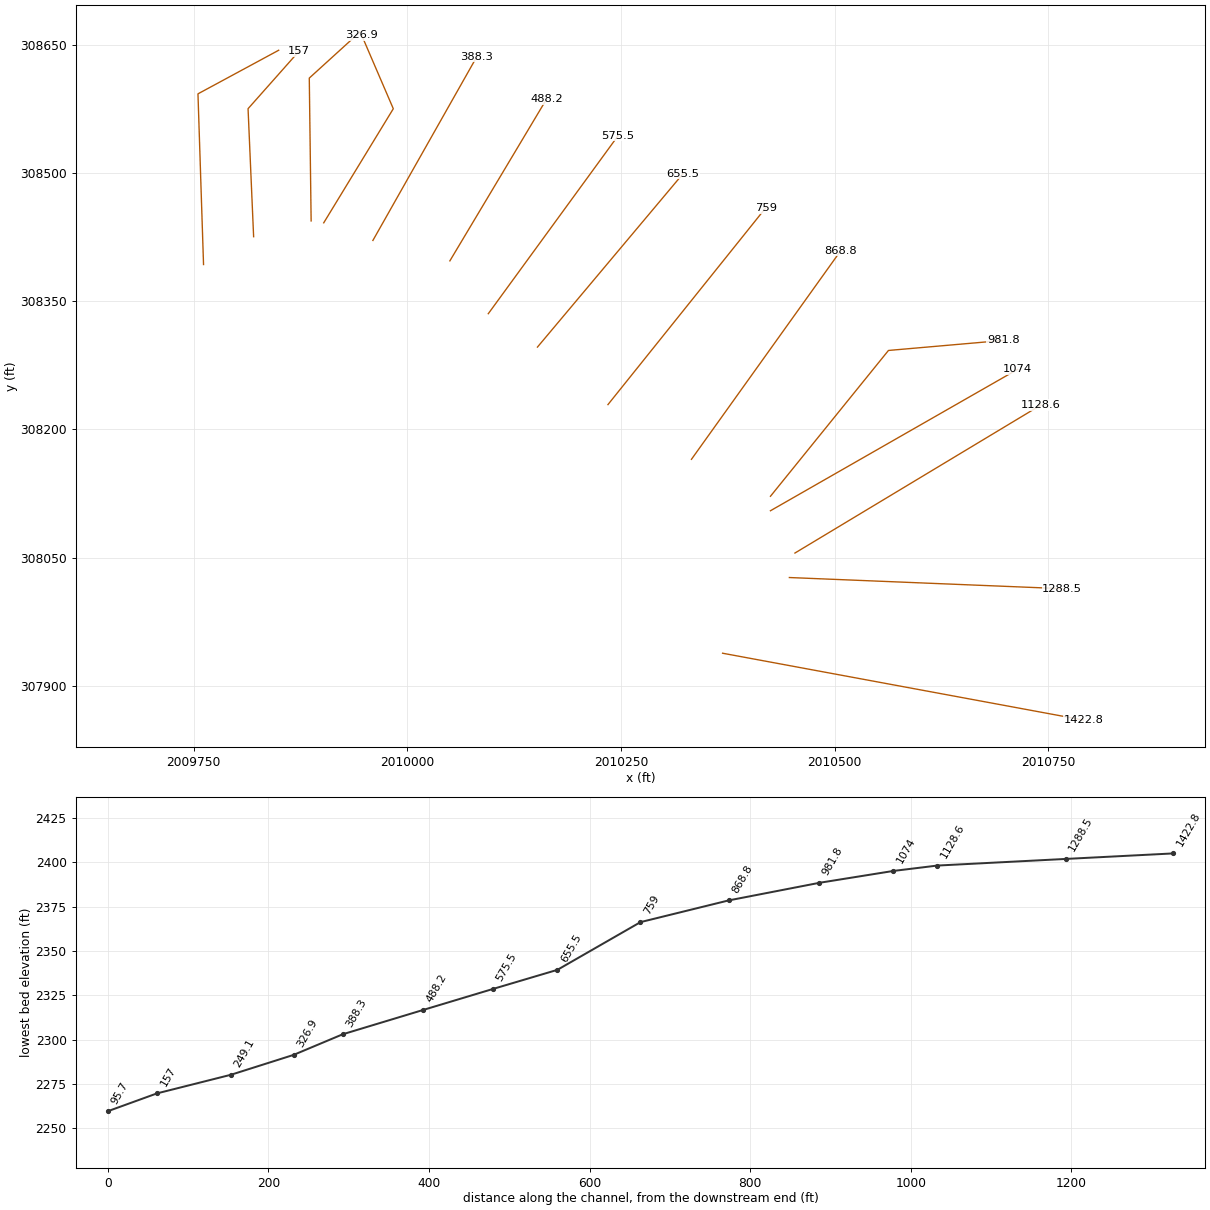
HEC-RAS study COONCK.prj: COONCK

--- COONCK.g01 (geometry) --- (continued)

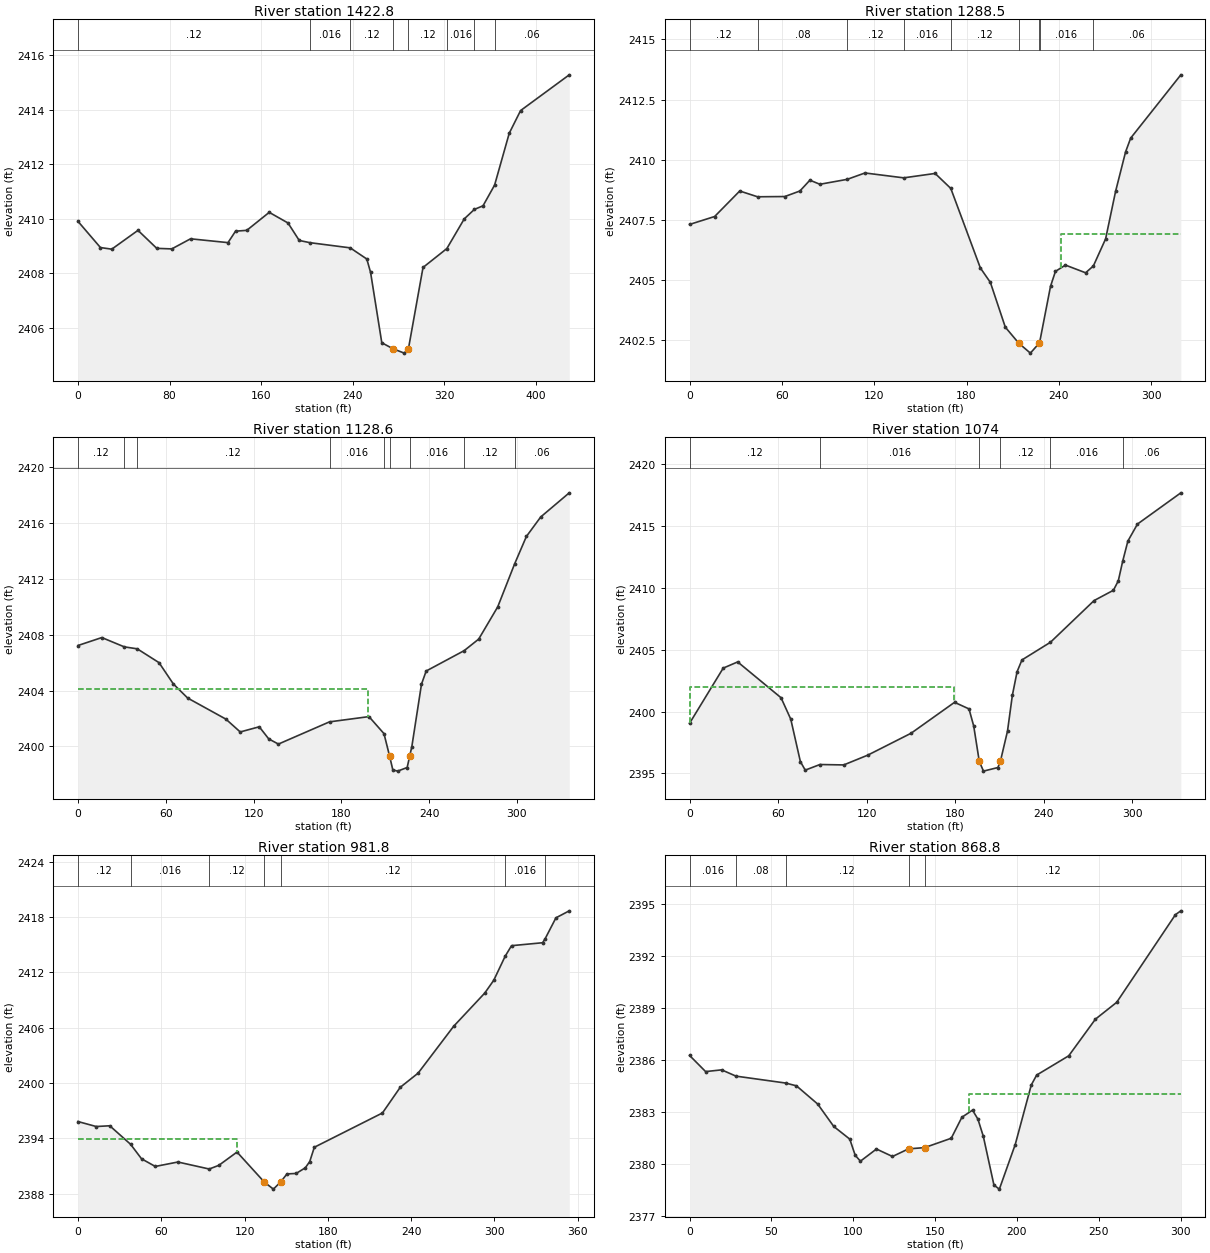
Type RM Length L Ch R = 1 ,1422.8  ,130.7,134.2,137.2
XS GIS Cut Line= 2
     2010368.881      307938.103     2010790.756      307859.978
#Sta/Elev= 30
       0 2409.91    19.6 2408.95    29.5 2408.89    52.4 2409.58    68.8 2408.92
    81.9  2408.9    98.3 2409.27     131 2409.13   137.6 2409.55   147.4 2409.58
     167 2410.24   183.4 2409.85   193.2 2409.21  202.592409.128  237.732408.938
   252.2 2408.53   255.5 2408.04   265.3 2405.46   275.1 2405.24   284.9 2405.08
  288.532405.231   301.3 2408.22   322.12408.912   337.3    2410  346.132410.347
   353.7 2410.48  363.812411.239   376.6 2413.14   386.5 2413.97     429 2415.28
#Mann= 8 ,-1 , 0
       0     .12       0  202.59    .016       0  237.73     .12       0
   275.1    .045       0  288.53     .12       0   322.1    .016       0
  346.13     .12       0  363.81     .06       0
Bank Sta=275.1,288.53
XS Rating Curve= 0 ,0
Exp/Cntr=0.3,0.1

Type RM Length L Ch R = 1 ,1288.5  ,146.6,159.9,172.9
XS GIS Cut Line= 2
     2010447.006      308026.645     2010766.017      308013.624
#Sta/Elev= 30
       0 2407.31    16.3 2407.64    32.6  2408.7   44.19 2408.46    61.9 2408.47
    71.7  2408.7    78.2 2409.15    84.7 2408.98  102.472409.185     114 2409.45
  139.162409.247   159.6 2409.43  169.782408.807     189  2405.5   195.5  2404.9
   205.2 2403.04  213.962402.373   221.5 2401.96   227.2 2402.37  227.492402.396
   234.6 2404.74   237.8 2405.36   244.3 2405.62   257.4  2405.3  262.442405.584
   270.4 2406.71   276.9 2408.69   283.4 2410.33   286.7  2410.9   319.3 2413.53
#Mann= 9 ,-1 , 0
       0     .12       0   44.19     .08       0  102.47     .12       0
  139.16    .016       0  169.78     .12       0  213.96    .045       0
   227.2     .12       0  227.49    .016       0  262.44     .06       0
#XS Ineff= 2 , 0
                          241.64         2406.93
Permanent Ineff=
       F       F
Bank Sta=213.96,227.2
XS Rating Curve= 0 ,0
Exp/Cntr=0.3,0.1

Type RM Length L Ch R = 1 ,1128.6  ,56.4,54.6,54
XS GIS Cut Line= 2
     2010453.517      308055.291     2010741.277      308228.468
#Sta/Elev= 30
       0 2407.23    16.3  2407.8   31.692407.131    40.52406.992    55.4    2406
    65.2 2404.47      75 2403.46   101.1 2401.95   110.9 2401.03   123.9  2401.4
   130.4 2400.53     137 2400.16  171.922401.754   198.9 2402.13  209.162400.909
  212.972399.307   215.2 2398.31   218.5 2398.22     225 2398.48  226.772399.313
   228.2 2399.98   234.8 2404.46     238  2405.4  263.972406.861   273.9 2407.69
   286.9    2410  298.44 2413.08   306.5 2415.05   316.3 2416.45   335.8 2418.18
#Mann= 9 ,-1 , 0
       0     .12       0   31.69     .08       0    40.5     .12       0
  171.92    .016       0  209.16     .12       0  212.97    .045       0
  226.77    .016       0  263.97     .12       0  298.44     .06       0
#XS Ineff= 2 , 0
           198.3 2404.12
Permanent Ineff=
       F       F
Bank Sta=212.97,226.77
XS Rating Curve= 0 ,0
Exp/Cntr=0.3,0.1

Type RM Length L Ch R = 1 ,1074    ,82.3,92.2,100.5
XS GIS Cut Line= 2
     2010424.871       308104.77     2010713.933      308270.134
#Sta/Elev= 30
       0 2399.05    22.8  2403.5    32.6    2404      62 2401.11    68.6 2399.38
    75.1 2395.96    78.4 2395.27   88.372395.723   104.5 2395.69   120.8 2396.48
   150.2 2398.25   179.6 2400.74   189.4 2400.21   192.6 2398.83  196.352395.988
   199.2 2395.19     209 2395.48   210.7 2395.99   215.5 2398.42   218.8 2401.31
     222 2403.21   225.3 2404.16  244.622405.586   274.2 2408.95   287.3 2409.78
   290.6 2410.54  293.562412.113   297.1 2413.75   303.6 2415.12     333 2417.64
#Mann= 6 ,-1 , 0
       0     .12       0   88.37    .016       0  196.35    .045       0
   210.7     .12       0  244.62    .016       0  293.56     .06       0
#XS Ineff= 2 , 0
          179.15 2401.97
Permanent Ineff=
       F       F
Bank Sta=196.35,210.7
XS Rating Curve= 0 ,0
Exp/Cntr=0.3,0.1

Type RM Length L Ch R = 1 ,981.8   ,111.1,113,114.1
XS GIS Cut Line= 3
     2010424.871      308121.697     2010562.892       308292.27
     2010697.006      308303.989
#Sta/Elev= 30
       0 2395.82    13.1 2395.28    22.9 2395.36   37.912393.351    45.8 2391.78
    55.7 2390.95      72 2391.43   94.562390.671   101.5 2391.07   114.6 2392.51
   134.3 2389.25   140.8 2388.49  146.112389.278   150.6 2390.14   157.2 2390.19
   163.8  2390.8     167 2391.48   170.3 2393.03   219.4 2396.75   232.2 2399.53
   245.1 2401.07   270.7 2406.15   293.1 2409.75   299.6 2411.14  307.83 2413.75
   312.4 2414.89   334.8 2415.21  336.662415.657   344.4 2417.91     354 2418.67
#Mann= 7 ,-1 , 0
       0     .12       0   37.91    .016       0   94.56     .12       0
   134.3    .045       0  146.11     .12       0  307.83    .016       0
  336.66     .06       0
#XS Ineff= 2 , 0
          114.34 2393.93
Permanent Ineff=
       F       F
Bank Sta=134.3,146.11
XS Rating Curve= 0 ,0
Exp/Cntr=0.3,0.1

Type RM Length L Ch R = 1 ,868.8   ,110.5,109.8,108.1
XS GIS Cut Line= 2
      2010332.44      308164.926     2010507.137      308409.067
#Sta/Elev= 30
       0 2386.26     9.8 2385.33    19.6 2385.43   28.342385.069   58.71 2384.67
    65.3 2384.51    78.3 2383.46    88.1 2382.17    97.9 2381.44   101.2 2380.51
   104.4 2380.17   114.2 2380.87     124 2380.44   133.8 2380.88   143.6 2380.95
   159.9 2381.49   166.4  2382.7   172.9 2383.11   176.2 2382.59   179.5  2381.6
     186 2378.79   189.3 2378.56     199 2381.13   208.8 2384.56   212.1 2385.13
   231.7 2386.24     248 2388.35     261 2389.32   296.9 2394.37   300.2 2394.59
#Mann= 5 ,-1 , 0
       0    .016       0   28.34     .08       0   58.71     .12       0
   133.8    .045       0   143.6     .12       0
#XS Ineff= 2 , 0
                          170.85         2384.02
Permanent Ineff=
       F       F
Bank Sta=133.8,143.6
XS Rating Curve= 0 ,0
Exp/Cntr=0.3,0.1

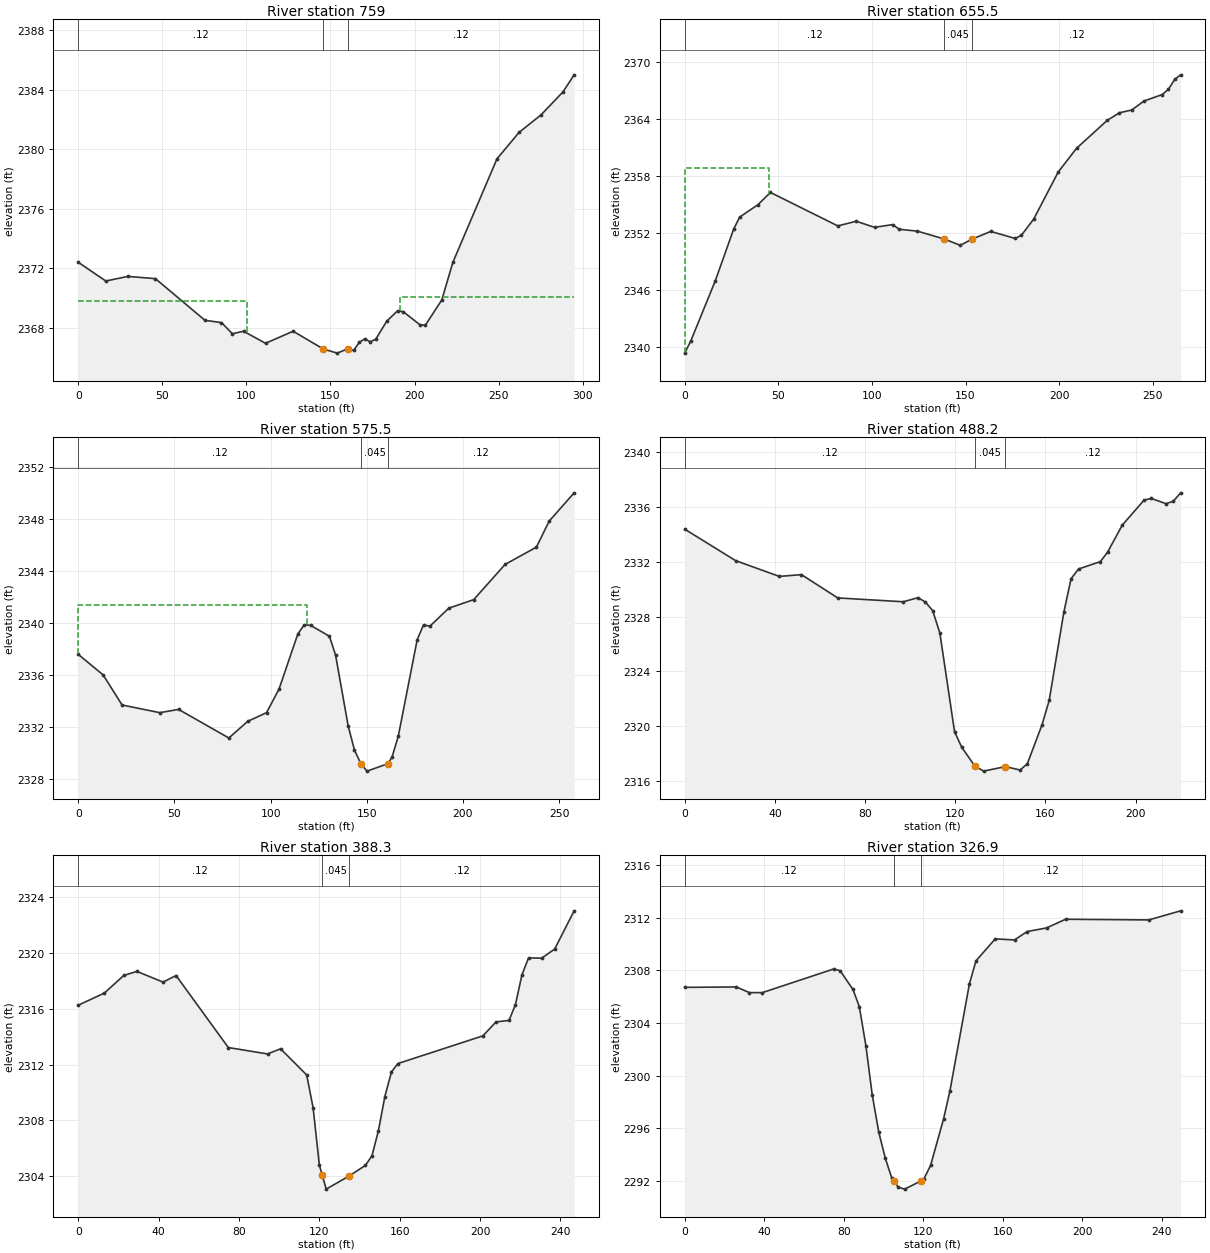
Type RM Length L Ch R = 1 ,759     ,103.9,103.5,102.9
XS GIS Cut Line= 2
     2010234.784      308228.945     2010419.246       308458.98
#Sta/Elev= 30
       0 2372.41    16.4 2371.15    29.5 2371.46    45.9 2371.31    75.4 2368.51
    85.2 2368.36    91.7 2367.61    98.3 2367.78   111.4 2366.97   127.8 2367.78
   145.7 2366.59     154 2366.31   160.5 2366.61   163.8 2366.49   167.1 2367.03
   170.4 2367.27   173.6 2367.07   176.9 2367.24   183.5 2368.46     190 2369.16
   193.3 2369.09   203.1 2368.22   206.4 2368.18   216.2 2369.88   222.8 2372.41
     249 2379.35   262.1 2381.12   275.2  2382.3   288.3 2383.85   294.9 2384.99
#Mann= 3 ,-1 , 0
       0     .12       0   145.7    .045       0   160.5     .12       0
#XS Ineff= 2 , 0
          100.31  2369.8  191.33          2370.1
Permanent Ineff=
       F       F
Bank Sta=145.7,160.5
XS Rating Curve= 0 ,0
Exp/Cntr=0.3,0.1

Type RM Length L Ch R = 1 ,655.5   ,78.3,80.1,81.3
XS GIS Cut Line= 2
     2010152.319      308296.219     2010322.675      308499.127
#Sta/Elev= 30
       0 2339.38     3.3 2340.68    16.4 2347.01    26.2 2352.44    29.4 2353.69
    39.2    2355    45.8 2356.28    81.8 2352.76    91.6 2353.25   101.4 2352.61
   111.2  2352.9   114.5 2352.41   124.3 2352.21   138.7 2351.38   147.2 2350.72
   153.7 2351.39   163.5 2352.18   176.6 2351.44   179.9 2351.79   186.4 2353.47
   199.5 2358.42   209.3 2360.92   225.7 2363.86   232.2 2364.66   238.8 2364.95
   245.3 2365.89   255.1 2366.58   258.4 2367.13   261.7 2368.16   264.9 2368.65
#Mann= 3 ,-1 , 0
       0     .12       0   138.7    .045       0   153.7     .12       0
#XS Ineff= 2 , 0
           44.89 2358.89
Permanent Ineff=
       F       F
Bank Sta=138.7,153.7
XS Rating Curve= 0 ,0
Exp/Cntr=0.3,0.1

Type RM Length L Ch R = 1 ,575.5   ,84.7,87.3,88.6
XS GIS Cut Line= 2
      2010094.81      308335.282      2010246.72      308543.615
#Sta/Elev= 30
       0 2337.61      13 2336.02    22.8 2333.71    42.4 2333.12    52.2 2333.37
    78.3 2331.17    88.1 2332.45    97.9 2333.12   104.4 2334.94   114.2 2339.19
   117.5 2339.88   120.8 2339.84   130.6    2339   133.8 2337.54   140.3 2332.12
   143.6 2330.24   146.9  2329.2   150.1 2328.62   161.12329.195   163.2 2329.73
   166.4 2331.32   176.2 2338.73   179.5 2339.88   182.8 2339.77   192.6 2341.16
   205.6 2341.82   221.9 2344.53   238.2 2345.86   244.8 2347.86   257.8 2350.04
#Mann= 3 ,-1 , 0
       0     .12       0   146.9    .045       0   161.1     .12       0
#XS Ineff= 2 , 0
          118.89 2341.37
Permanent Ineff=
       F       F
Bank Sta=146.9,161.1
XS Rating Curve= 0 ,0
Exp/Cntr=0.3,0.1

Type RM Length L Ch R = 1 ,488.2   ,98.6,99.8,98.3
XS GIS Cut Line= 2
     2010049.871      308397.088     2010162.718       308585.89
#Sta/Elev= 30
       0 2334.38    22.6 2332.08      42 2330.93    51.8 2331.06    67.9 2329.36
      97 2329.08   103.5 2329.38   106.7 2329.07     110 2328.44   113.2  2326.8
   119.7 2319.61   122.9 2318.46  128.652317.105   132.6 2316.72   142.3 2317.05
   148.8  2316.8     152 2317.26   158.5 2320.09   161.7 2321.88   168.2 2328.32
   171.4 2330.76   174.7 2331.47   184.4 2332.01   187.6  2332.7   194.1 2334.67
   203.8  2336.5     207 2336.62   213.5 2336.24   216.7 2336.41     220 2337.03
#Mann= 3 ,-1 , 0
       0     .12       0  128.65    .045       0   142.3     .12       0
Bank Sta=128.65,142.3
XS Rating Curve= 0 ,0
Exp/Cntr=0.3,0.1

Type RM Length L Ch R = 1 ,388.3   ,66.2,61.4,61.8
XS GIS Cut Line= 2
      2009959.81      308420.959     2010081.338      308635.803
#Sta/Elev= 30
       0 2316.26      13 2317.13    22.7  2318.4    29.2 2318.69    42.2 2317.92
    48.7 2318.39    74.7 2313.22    94.2 2312.76   100.7 2313.13   113.7 2311.25
   116.9 2308.89     120 2304.78   121.42304.068   123.4 2303.05  134.982304.008
   142.9 2304.75   146.2 2305.45   149.4 2307.25   152.6  2309.7   155.9 2311.47
   159.1 2312.07   201.4 2314.06   207.9 2315.06   214.4 2315.17   217.6 2316.31
   220.8 2318.43   224.1 2319.66   230.6 2319.64   237.1 2320.29   246.8 2323.04
#Mann= 3 ,-1 , 0
       0     .12       0   121.4    .045       0  134.98     .12       0
Bank Sta=121.4,134.98
XS Rating Curve= 0 ,0
Exp/Cntr=0.3,0.1

Type RM Length L Ch R = 1 ,326.9   ,69.8,77.8,90.2
XS GIS Cut Line= 3
     2009902.301      308441.575     2009983.682      308575.039
     2009946.789      308660.759
#Sta/Elev= 30
       0  2306.7      26 2306.73    32.6  2306.3    39.1  2306.3    74.9 2308.09
    78.2 2307.97    84.7 2306.54    87.9 2305.23    91.2 2302.27    94.4 2298.53
    97.7 2295.69     101 2293.71   104.2 2292.24  105.292292.006   107.5 2291.53
   110.7 2291.38  118.992292.006   120.5 2292.18   123.8  2293.2   130.3 2296.71
   133.5 2298.84   143.3 2306.96   146.6 2308.71   156.3 2310.38     166  2310.3
   172.4 2310.94   182.1 2311.21   191.7 2311.87   233.6 2311.82   249.6 2312.51
#Mann= 3 ,-1 , 0
       0     .12       0  105.29    .045       0  118.99     .12       0
Bank Sta=105.29,118.99
XS Rating Curve= 0 ,0
Exp/Cntr=0.3,0.1

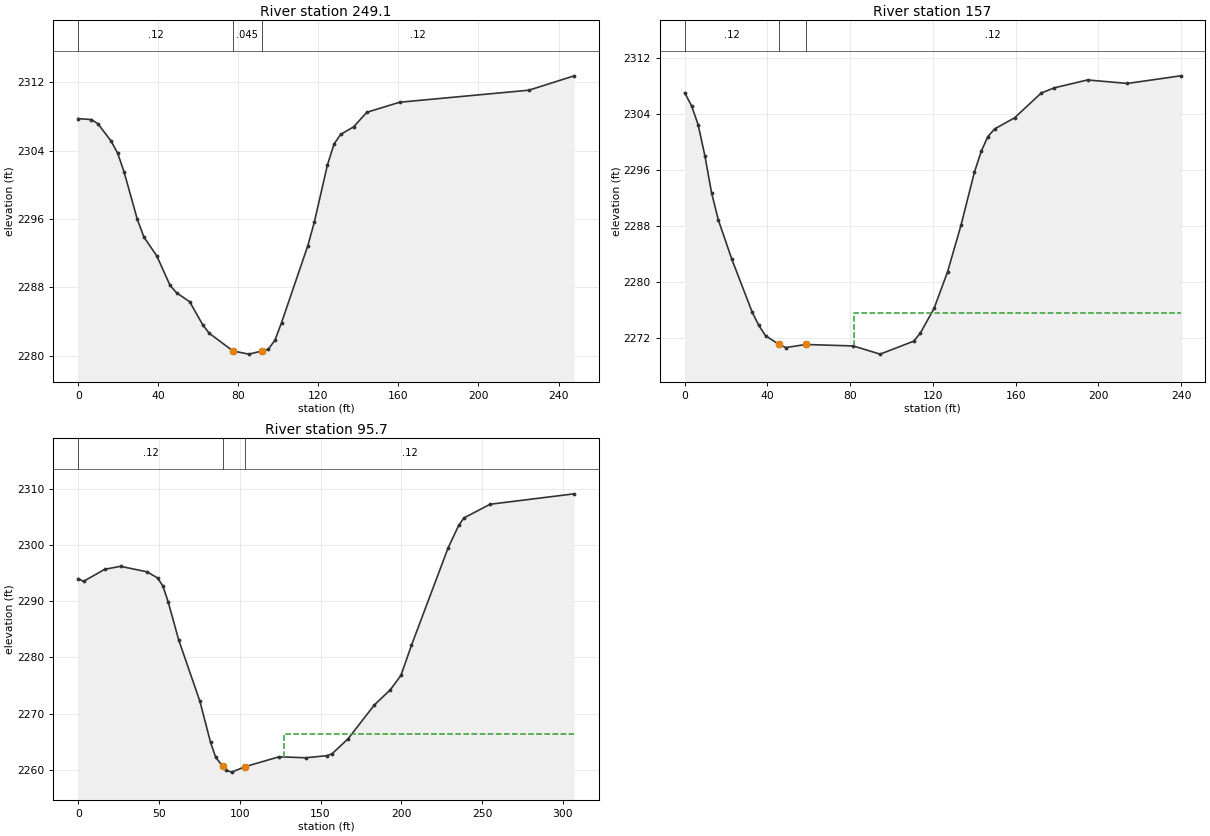
Type RM Length L Ch R = 1 ,249.1   ,81,92.2,92.6
XS GIS Cut Line= 3
     2009887.562      308443.789     2009885.392       308610.89
     2009945.071      308665.143
#Sta/Elev= 30
       0 2307.76     6.6 2307.65     9.8 2307.17    16.4 2305.15    19.7 2303.72
    22.9 2301.54    29.5    2296    32.8 2293.91    39.3 2291.68    45.9 2288.24
    49.2 2287.37    55.7 2286.33    62.3  2283.6    65.5 2282.64    77.32280.574
    85.2  2280.2    91.8 2280.56      95 2280.78    98.3 2281.83   101.6 2283.89
   114.7 2292.87     118 2295.67   124.5 2302.32   127.8 2304.77   131.1 2305.91
   137.6  2306.8   144.2  2308.5   160.6 2309.68   225.2 2311.09   247.8 2312.77
#Mann= 3 ,-1 , 0
       0     .12       0    77.3    .045       0    91.8     .12       0
Bank Sta=77.3,91.8
XS Rating Curve= 0 ,0
Exp/Cntr=0.3,0.1

Type RM Length L Ch R = 1 ,157     ,61.2,61.3,60.6
XS GIS Cut Line= 3
     2009820.288      308425.343     2009813.777      308575.082
     2009873.456      308642.357
#Sta/Elev= 30
       0 2307.06     3.3 2305.21     6.5  2302.5     9.8    2298      13 2292.75
    16.3 2288.84    22.8 2283.25    32.6 2275.71    35.8 2273.81    39.1 2272.31
    45.6 2271.07    48.9 2270.62    58.6 2271.06    81.5 2270.85    94.5 2269.68
   110.8 2271.54     114 2272.72   120.6 2276.23   127.1 2281.44   133.6  2288.1
   140.1 2295.71   143.4 2298.68   146.6  2300.8   149.9 2301.89   159.5 2303.47
   172.4 2307.02   178.8 2307.77   194.8 2308.89   214.1 2308.39   239.8 2309.48
#Mann= 3 ,-1 , 0
       0     .12       0    45.6    .045       0    58.6     .12       0
#XS Ineff= 2 , 0
                           82.04         2275.54
Permanent Ineff=
       F       F
Bank Sta=45.6,58.6
XS Rating Curve= 0 ,0
Exp/Cntr=0.3,0.1

Type RM Length L Ch R = 1 ,95.7    ,58.7,59.9,60.5
XS GIS Cut Line= 3
     2009761.694      308392.791     2009755.183      308592.443
     2009849.584      308643.442
#Sta/Elev= 30
       0 2293.99     3.3 2293.51    16.4 2295.65    26.2 2296.18    42.6  2295.2
    49.1 2294.12    52.4 2292.69    55.7 2289.85    62.2  2283.1    75.3 2272.22
    81.9 2264.93    85.1 2262.24   89.382260.665    91.7 2259.92      95 2259.61
  103.512260.598   124.4 2262.34   140.8 2262.16   153.9 2262.53   157.2 2262.89
     167 2265.52   183.4 2271.57   193.2 2274.24   199.8 2276.81   206.3 2282.15
     229 2299.47   235.5 2303.44   238.8 2304.78     255 2307.21     307 2309.06
#Mann= 3 ,-1 , 0
       0     .12       0   89.38    .045       0  103.51     .12       0
#XS Ineff= 2 , 0
                           127.5         2266.32
Permanent Ineff=
       F       F
Bank Sta=89.38,103.51
XS Rating Curve= 0 ,0
Exp/Cntr=0.3,0.1