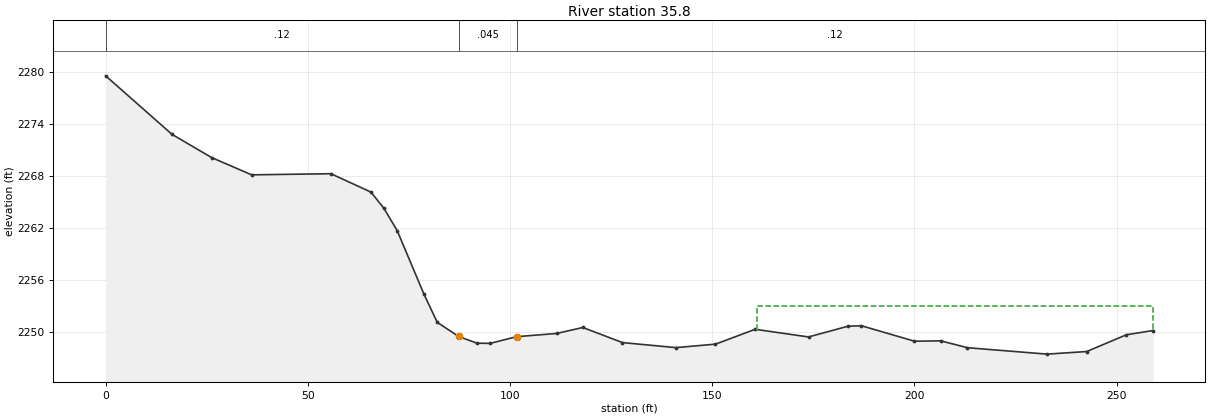
HEC-RAS study COONCK.prj: COONCK

--- COONCK.g01 (geometry) --- (continued)

Type RM Length L Ch R = 1 ,35.8    ,39.9,35.8,31.1
XS GIS Cut Line= 2
     2009708.074      308381.897     2009688.543      308640.143
#Sta/Elev= 30
       0 2279.52    16.4 2272.78    26.2  2270.1    36.1 2268.11    55.7 2268.24
    65.6 2266.12    68.8 2264.26    72.1 2261.67    78.7 2254.37      82 2251.11
    87.32249.483    91.8 2248.71    95.1 2248.69   101.6 2249.46   111.5 2249.83
     118 2250.52   127.8 2248.78     141  2248.2   150.8  2248.6   160.6 2250.31
   173.8 2249.43   183.6 2250.67   186.9 2250.72     200 2248.94   206.5 2248.98
   213.1 2248.19   232.8 2247.45   242.6 2247.75   252.4 2249.68     259 2250.17
#Mann= 3 ,-1 , 0
       0     .12       0    87.3    .045       0   101.6     .12       0
#XS Ineff= 2 , 0
                          160.99         2252.98
Permanent Ineff=
       F       F
Bank Sta=87.3,101.6
XS Rating Curve= 0 ,0
Exp/Cntr=0.3,0.1

Chan Stop Cuts=-1
Use User Specified Reach Order=0
Composite Channel Slope=5